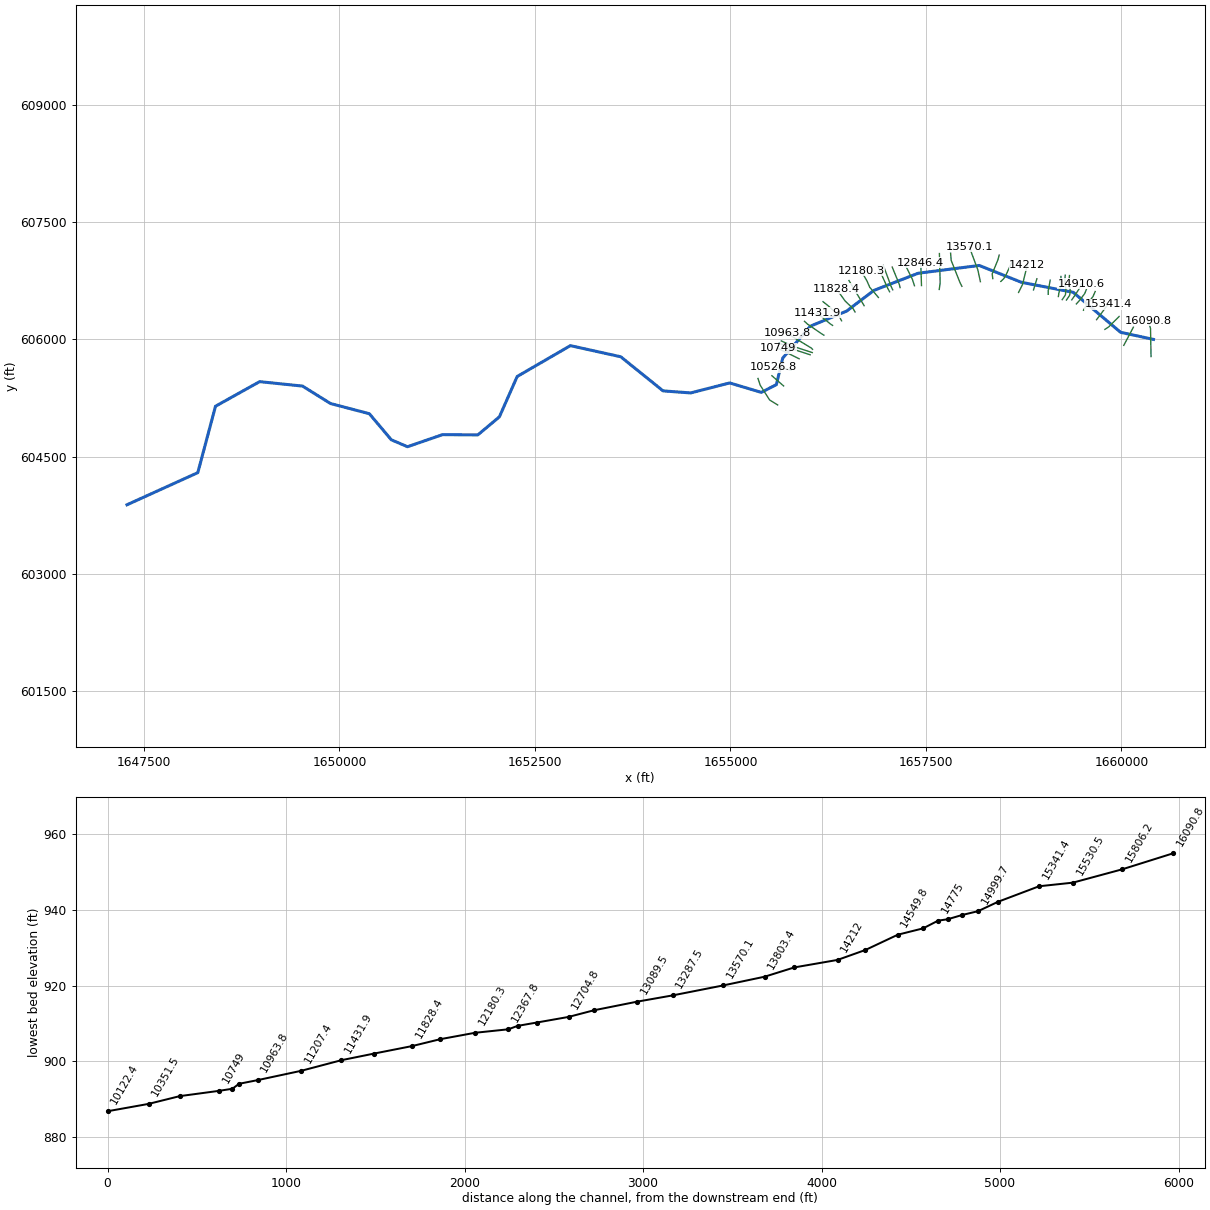
--- NFSHORTCRK.prj (project) ---

Proj Title=NFSHORTCRK
Current Plan=p01
Default Exp/Contr=0,0
English Units
Geom File=g01
Flow File=f01
Plan File=p01
BEGIN DESCRIPTION:
END DESCRIPTION:
DSS Export Rating Curves= 0
DSS Export Rating Curve Sorted= 0
DSS Export Volume Flow Curves= 0
DXF OffsetX= 0
DXF OffsetY= 0
DXF ScaleX= 0
DXF ScaleY= 0

--- NFSHORTCRK.p01 (plan) ---

Plan Title=Floodplain
Program Version=4.00
Geom File=g01
Flow File=f01
K Sum by GR=0
Std Step Tol=0.01
Critical Tol=0.01
Num of Std Step Trials=20
Max Error Tol=0.3
Flow Tol Ratio=0.001
Split Flow NTrial=30
Split Flow Tol=0.02
Split Flow Ratio=0.02
Log Output Level=0
Friction Slope Method=1
Unsteady Friction Slope Method=2
Unsteady Bridges Friction Slope Method=1
Global Log Level=0
CheckData=False
Run HTab=0
Run UNet=0
Run PostProcess=0
UNET Theta=0
UNET Theta Warmup=0
UNET ZTol=0
UNET ZSATol=0
UNET MxIter=0
UNET MaxInSteps=0
UNET DtIC=0
UNET DtMin=0
UNET MaxCRTS=0
UNET WFStab=0
UNET SFStab=0
UNET WFX=0
UNET SFX=0
UNET DSS MLevel=0
UNET DZMax Abort=0
UNET Convert EG Bridges=0
UNET Use Existing IB Tables=0
UNET Froude Limit=0
UNET Froude Power=0
Write IC File=0
Echo Input=False
Echo Output=False
Write Detailed=0

--- NFSHORTCRK.f01 (steady flow) ---

Flow Title=NFF Regression Equation
Program Version=4.10
Number of Profiles= 1
Profile Names=P100yr
River Rch & RM=NFSHORTCRK,Main            ,16090.8
1129.807
River Rch & RM=NFSHORTCRK,Main            ,14999.7
1146.703
River Rch & RM=NFSHORTCRK,Main            ,14549.8
1336.209
River Rch & RM=NFSHORTCRK,Main            ,13570.1
1521.597
River Rch & RM=NFSHORTCRK,Main            ,10122.4
1602.642
River Rch & RM=NFSHORTCRK,Main            ,9985
1814.774
River Rch & RM=NFSHORTCRK,Main            ,8547.9
1835.128
River Rch & RM=NFSHORTCRK,Main            ,8172.7
2074.208
River Rch & RM=NFSHORTCRK,Main            ,6884.7
2218.644
River Rch & RM=NFSHORTCRK,Main            ,368.3
 2407.49
Boundary for River Rch & Prof#=NFSHORTCRK,Main            , 1
Up Type= 0
Dn Type= 3
Dn Slope=0.01
DSS Import GetInterval= 0
DSS Import GetPeak= 0
DSS Import FillOption= 0

--- NFSHORTCRK.g01 (geometry) ---

Geom Title=USGS 10m DEM
Program Version=4.10

River Reach=NFSHORTCRK      ,Main
Reach XY= 30
     1660408.831      605998.885     1659988.692      606089.163
     1659382.789      606600.447     1658721.331      606728.052
       1658181.4      606943.329     1657401.018      606844.371
     1656834.178      606624.753     1656484.352      606359.996
     1656022.066      606167.756     1655668.379       605760.17
     1655586.782       605420.76     1655394.074      605321.802
     1654989.907      605442.461     1654491.296      605314.857
     1654137.997      605340.899     1653597.199      605776.663
     1652953.102      605919.024     1652272.546      605524.927
     1652045.115      605009.302     1651769.074      604778.399
     1651317.685      604781.871     1650869.768      604627.357
     1650663.171      604715.899     1650381.921      605049.232
     1649885.393      605179.441     1649528.142      605402.131
     1648979.143      605458.954     1648414.907      605144.718
     1648188.733      604296.228     1647283.047      603885.551

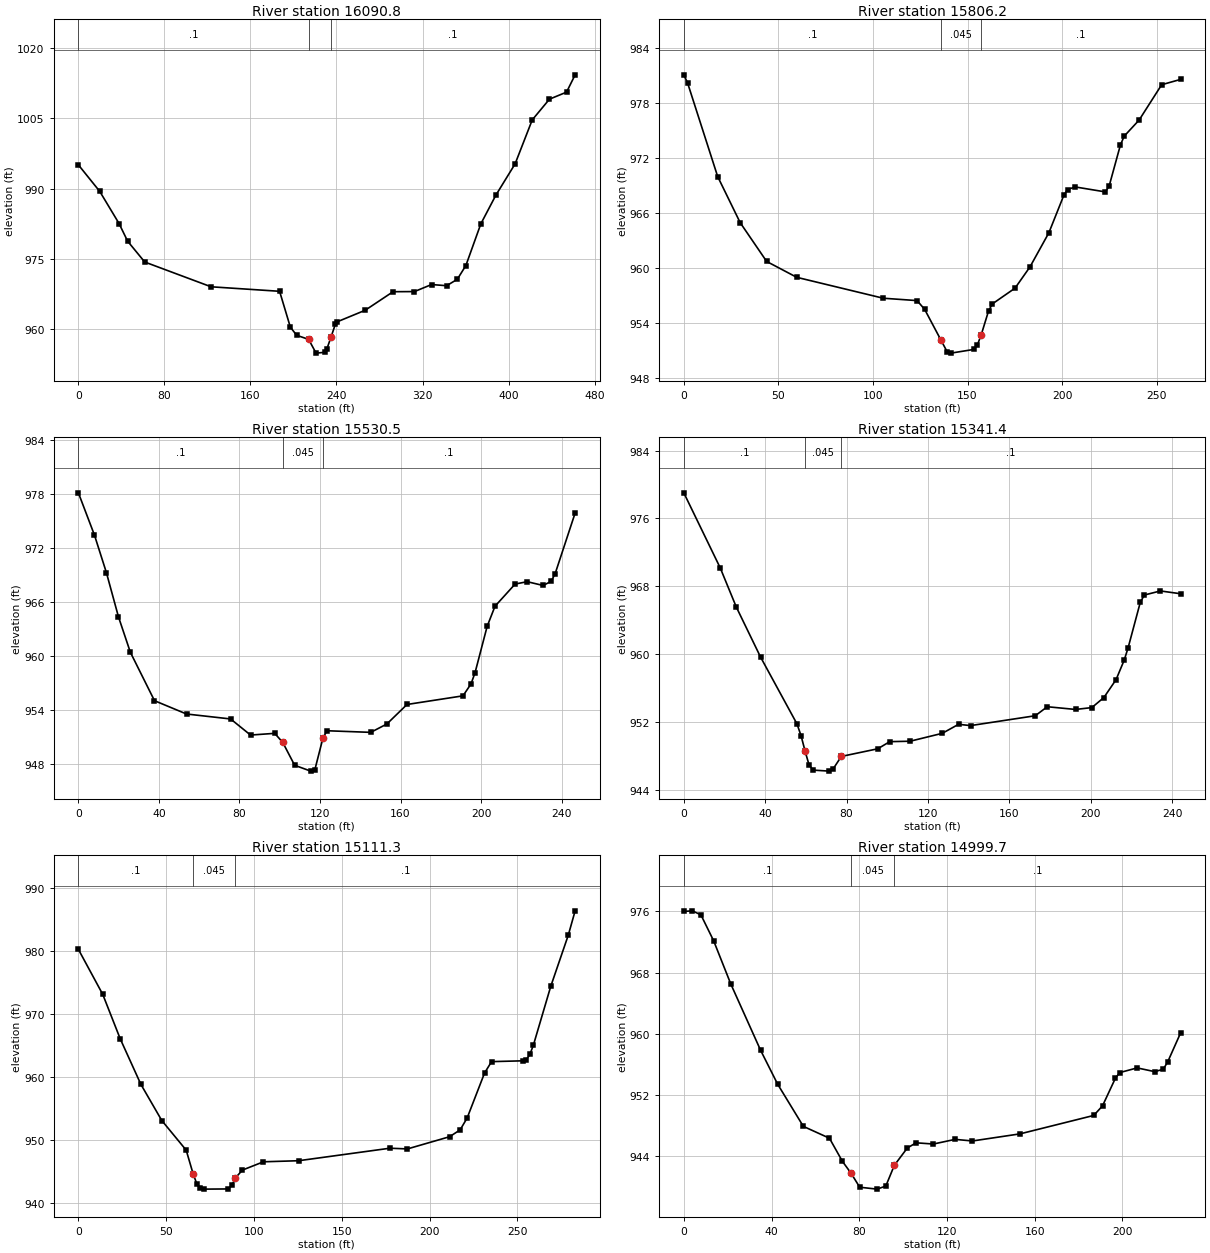
Type RM Length L Ch R = 1 ,16090.8 ,295.9,284.5,271.8
XS GIS Cut Line= 3
     1660377.769       605779.52     1660371.258      606139.763
     1660339.791      606236.334
#Sta/Elev= 30
       0  995.08    19.9  989.41    37.8  982.58    45.8  978.81    61.7  974.37
   123.4  969.09   187.1  968.13   197.1  960.48     203  958.75   214.1  957.88
     221  954.95   228.9  955.12   230.9  955.74   234.9  958.37   238.9  961.07
   240.9  961.65   266.7  964.09   292.6  968.04   312.5  968.07   328.4  969.57
   342.4  969.32   352.3  970.68   360.3  973.62   374.2   982.5   388.2  988.62
   406.1   995.3     422 1004.66     438 1009.08   453.9 1010.58   461.9 1014.27
#Mann= 3 , 0 , 0
       0      .1       0   214.1    .045       0   234.9      .1       0
Bank Sta=214.1,234.9
XS Rating Curve= 0 ,0
Exp/Cntr=0.3,0.1

Type RM Length L Ch R = 1 ,15806.2 ,281.5,275.8,269.2
XS GIS Cut Line= 2
     1660029.462      605922.749     1660152.074      606154.954
#Sta/Elev= 30
       0  981.09       2   980.2    17.9  969.99    29.8  964.96    43.8  960.73
    59.7     959   105.4  956.72   123.3  956.46   127.3  955.51   135.9  952.16
   139.2  950.88   141.2  950.73   153.2  951.13   155.2  951.63   157.2  952.72
   161.1  955.34   163.1   956.1   175.1  957.82     183  960.14     193  963.87
   200.9  967.96   202.9  968.58   206.9  968.86   222.8  968.32   224.8  968.93
   230.8  973.44   232.8   974.4   240.7  976.16   252.6  980.01   262.6  980.59
#Mann= 3 , 0 , 0
       0      .1       0   135.9    .045       0   157.2      .1       0
Bank Sta=135.9,157.2
XS Rating Curve= 0 ,0
Exp/Cntr=0.3,0.1

Type RM Length L Ch R = 1 ,15530.5 ,185.6,189,192.6
XS GIS Cut Line= 4
     1659787.491      606126.742     1659834.149      606157.124
     1659931.805      606253.695     1659969.783      606291.673
#Sta/Elev= 30
       0  978.15       8  973.44    13.9  969.29    19.9  964.37    25.8  960.43
    37.8  955.04    53.7  953.56    75.6  953.01    85.5  951.22    97.5  951.41
   101.5   950.4   107.4  947.86   115.4  947.21   117.4  947.33   121.4  950.84
   123.4   951.7   145.2  951.52   153.2  952.45   163.2  954.62     191  955.58
     195  956.91     197  958.16     203   963.3   206.9  965.54   216.9  968.01
   222.9  968.27   230.8  967.85   234.8  968.31   236.8  969.18   246.7  975.91
#Mann= 3 , 0 , 0
       0      .1       0   101.5    .045       0   121.4      .1       0
Bank Sta=101.5,121.4
XS Rating Curve= 0 ,0
Exp/Cntr=0.3,0.1

Type RM Length L Ch R = 1 ,15341.4 ,228.8,230.1,229.2
XS GIS Cut Line= 2
     1659681.154       606250.44     1659827.639      606445.753
#Sta/Elev= 30
       0  979.02    17.9  970.18    25.8  965.57    37.7  959.69    55.6  951.82
    57.6  950.44    59.6  948.61    61.5  947.02    63.5  946.38    71.5  946.26
    73.4  946.53    77.4  947.99    95.3  948.89   101.2  949.73   111.2  949.78
     127  950.71     135  951.77   140.9  951.62   172.7  952.78   178.6  953.84
   192.5  953.52   200.5  953.74   206.4  954.92   212.4  957.03   216.4  959.33
   218.3  960.76   224.3  966.13   226.3  966.99   234.2  967.47   244.1  967.14
#Mann= 3 , 0 , 0
       0      .1       0    59.6    .045       0    77.4      .1       0
Bank Sta=59.6,77.4
XS Rating Curve= 0 ,0
Exp/Cntr=0.3,0.1

Type RM Length L Ch R = 1 ,15111.3 ,112,111.7,111.1
XS GIS Cut Line= 4
     1659514.054      606371.968     1659542.265      606419.711
     1659636.666      606548.834     1659663.793      606610.683
#Sta/Elev= 30
       0  980.31    13.9  973.13    23.8  966.09    35.6  958.82    47.5  953.07
    61.4  948.35    65.4  944.53    67.4  943.04    69.4  942.29    71.4  942.15
    85.4  942.18    87.4  942.75    89.4  943.92    93.4  945.18   105.4   946.5
   125.4  946.67   177.4  948.66   187.4  948.55   211.4  950.49   217.4  951.58
   221.4  953.47   231.3  960.62   235.3  962.44   253.2  962.57   255.1  962.76
   257.1  963.58   259.1  965.04     269  974.41     279  982.57   282.9  986.44
#Mann= 3 , 0 , 0
       0      .1       0    65.4    .045       0    89.4      .1       0
Bank Sta=65.4,89.4
XS Rating Curve= 0 ,0
Exp/Cntr=0.3,0.1

Type RM Length L Ch R = 1 ,14999.7 ,87.4,89,90.6
XS GIS Cut Line= 4
     1659422.908      606452.263       1659459.8      606492.411
     1659529.244      606583.557     1659550.946      606636.725
#Sta/Elev= 30
       0     976     3.9  976.08     7.8  975.55    13.6  972.16    21.4  966.52
      35  957.84    42.8  953.39    54.5  947.88    66.4  946.33    72.3  943.31
    76.3  941.73    80.2  939.92    88.1  939.67    92.1  940.07      96  942.79
   101.9  945.05   105.9  945.73   113.8  945.57   123.7  946.18   131.6  945.97
   153.3   946.9   186.9  949.31   190.9  950.56   196.8  954.19   198.8  954.92
   206.7  955.53   214.7  955.04   218.6  955.35   220.6   956.3   226.5   960.1
#Mann= 3 , 0 , 0
       0      .1       0    76.3    .045       0      96      .1       0
Bank Sta=76.3,96
XS Rating Curve= 0 ,0
Exp/Cntr=0.3,0.1

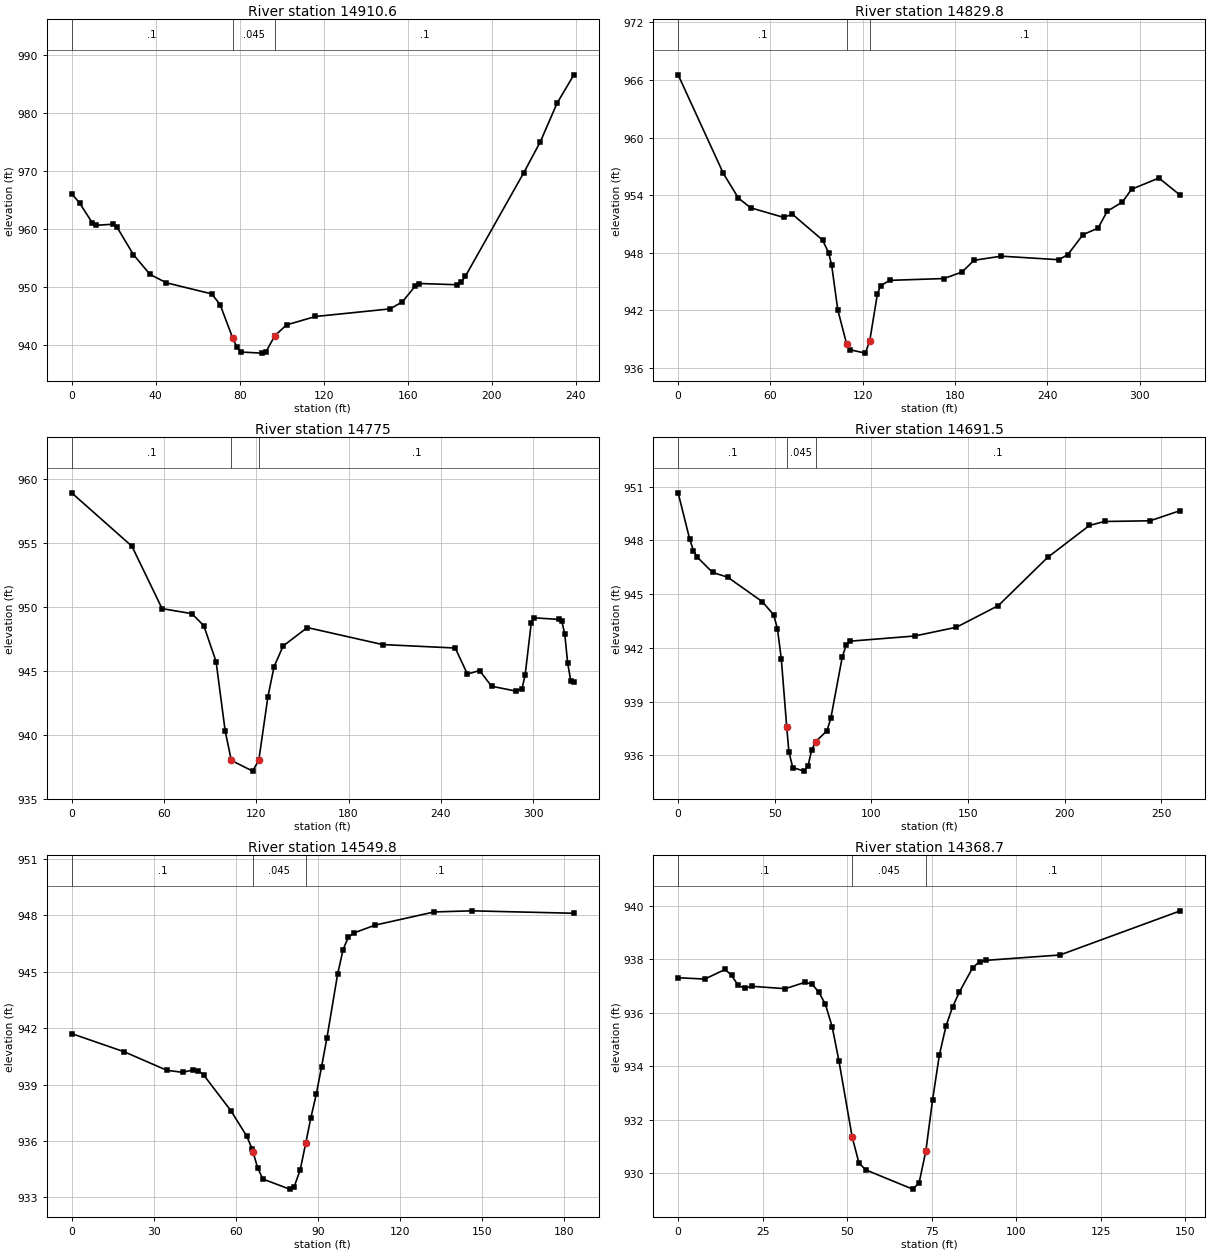
Type RM Length L Ch R = 1 ,14910.6 ,69.5,80.8,92.2
XS GIS Cut Line= 4
     1659364.314      606504.346     1659399.036       606554.26
      1659453.29      606636.725     1659488.012       606708.34
#Sta/Elev= 30
       0  966.13     3.9  964.45     9.8  961.11    11.8  960.68    19.6  960.86
    21.6  960.35    29.4  955.63    37.3  952.22    45.1  950.77    66.7  948.86
    70.7     947    76.6  941.34    78.6  939.73    80.5  938.85    90.4  938.66
    92.4  938.81    96.7  941.64   102.3  943.52   116.1  944.97   151.6  946.28
   157.5   947.5   163.5  950.18   165.5  950.65   183.4  950.44   185.4  950.86
   187.4  951.86   215.2  969.69   223.2   975.1   231.1  981.69   239.1  986.59
#Mann= 3 , 0 , 0
       0      .1       0    76.6    .045       0    96.7      .1       0
Bank Sta=76.6,96.7
XS Rating Curve= 0 ,0
Exp/Cntr=0.3,0.1

Type RM Length L Ch R = 1 ,14829.8 ,54.7,54.7,54
XS GIS Cut Line= 6
     1659295.955      606502.176     1659335.017        606558.6
     1659338.272      606569.451     1659343.698      606624.789
     1659329.592      606761.508     1659335.017      606814.676
#Sta/Elev= 30
       0  966.53    29.4  956.26    39.2  953.69    47.1  952.68    68.6  951.68
    74.3  952.01    93.9  949.32    97.8  948.02    99.8  946.74   103.8  942.05
   109.6  938.47   111.7  937.89   121.7  937.54   124.6  938.84   129.6  943.73
   131.6  944.55   137.5  945.12   172.8  945.31   184.5  945.98   192.4  947.21
   210.1  947.64   247.5  947.27   253.4   947.8   263.2  949.88     273  950.56
     279  952.32   288.9  953.29   294.8  954.61   312.6  955.78   326.5  953.98
#Mann= 3 , 0 , 0
       0      .1       0   109.6    .045       0   124.6      .1       0
Bank Sta=109.6,124.6
XS Rating Curve= 0 ,0
Exp/Cntr=0.3,0.1

Type RM Length L Ch R = 1 ,14775   ,86.2,83.6,80.3
XS GIS Cut Line= 6
     1659241.701      606506.517     1659280.764       606562.94
     1659284.019      606573.791     1659289.444      606629.129
     1659275.338      606765.848     1659280.764      606819.017
#Sta/Elev= 30
       0  958.92    39.2  954.74    58.8  949.86    78.1  949.47    85.9  948.53
    93.9  945.72    99.8   940.3   103.8  937.99   117.7  937.15   121.7  938.02
   127.6  942.97   131.6  945.32   137.5  946.94   153.2  948.38   202.2  947.05
   249.4  946.78   257.3  944.74   265.2  945.02     273  943.79   288.9  943.41
   292.8  943.61   294.8  944.64   298.8  948.73   300.8  949.14   316.6  949.02
   318.6  948.91   320.6  947.88   322.5  945.59   324.5  944.22   326.5  944.13
#Mann= 3 , 0 , 0
       0      .1       0   103.8    .045       0   121.7      .1       0
Bank Sta=103.8,121.7
XS Rating Curve= 0 ,0
Exp/Cntr=0.3,0.1

Type RM Length L Ch R = 1 ,14691.5 ,141,141.7,142.6
XS GIS Cut Line= 4
     1659192.873      606546.664     1659200.468      606595.492
      1659226.51      606700.744     1659225.425      606802.741
#Sta/Elev= 30
       0  950.65     5.9   948.1     7.9  947.43     9.9  947.06    17.8  946.21
    25.7  945.94    43.5  944.58    49.4  943.85    51.4  943.06    53.4  941.36
    56.2  937.56    57.3  936.21    59.3  935.32    65.2  935.12    67.2  935.41
    69.1   936.3    71.2  936.77      77  937.37      79  938.07    84.9  941.48
    86.9  942.14    88.8  942.37   122.4  942.66     144  943.15   165.7  944.36
   191.2  947.05   212.8  948.83   220.6  949.05   244.2  949.09   259.8  949.66
#Mann= 3 , 0 , 0
       0      .1       0    56.2    .045       0    71.2      .1       0
Bank Sta=56.2,71.2
XS Rating Curve= 0 ,0
Exp/Cntr=0.3,0.1

Type RM Length L Ch R = 1 ,14549.8 ,183.2,181.1,178.6
XS GIS Cut Line= 4
     1659062.665      606574.876     1659062.665      606619.364
      1659072.43      606669.277     1659088.706      606756.083
#Sta/Elev= 29
       0  941.71    19.3  940.74    34.8  939.76    40.6  939.65    44.5  939.78
    46.4  939.74    48.4  939.49    58.2  937.62      64  936.27      66  935.59
    66.4  935.39      68  934.59    69.9  933.98    79.7  933.44    81.4  933.57
    83.6  934.46    85.6  935.87    87.5  937.23    89.5   938.5    91.4  939.93
    93.4   941.5    97.3  944.88    99.3  946.18   101.2  946.84   103.2  947.06
     111  947.48   132.6  948.18   146.4  948.24   183.7  948.11
#Mann= 3 , 0 , 0
       0      .1       0    66.4    .045       0    85.6      .1       0
Bank Sta=66.4,85.6
XS Rating Curve= 0 ,0
Exp/Cntr=0.3,0.1

Type RM Length L Ch R = 1 ,14368.7 ,155.4,156.7,157.8
XS GIS Cut Line= 2
     1658874.948        606631.3      1658918.35      606773.444
#Sta/Elev= 30
       0  937.31     7.9  937.26    13.9  937.62    15.8   937.4    17.8  937.02
    19.8  936.92    21.8  936.99    31.7   936.9    37.6  937.14    39.6  937.07
    41.6  936.78    43.6  936.31    45.6  935.47    47.6  934.19    51.5  931.36
    53.5  930.39    55.5  930.13    69.4  929.41    71.3  929.64    73.3  930.83
    75.3  932.75    77.3  934.42    79.3  935.52    81.2  936.21    83.2  936.77
    87.2  937.69    89.2  937.91    91.2  937.96     113  938.16   148.6  939.81
#Mann= 3 , 0 , 0
       0      .1       0    51.5    .045       0    73.3      .1       0
Bank Sta=51.5,73.3
XS Rating Curve= 0 ,0
Exp/Cntr=0.3,0.1

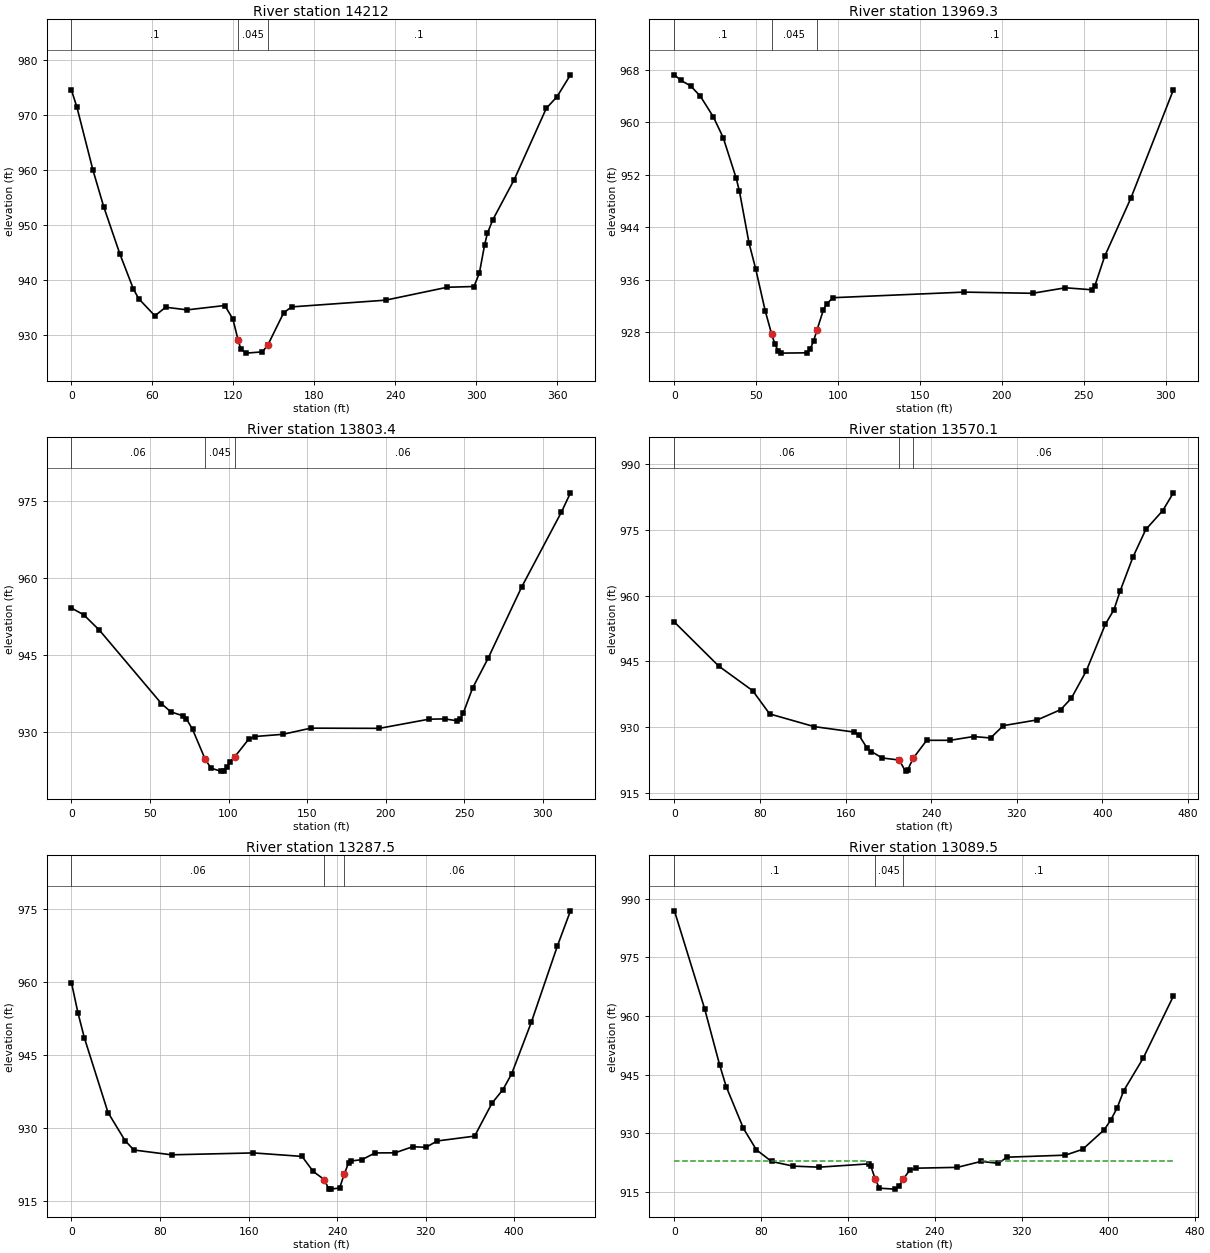
Type RM Length L Ch R = 1 ,14212   ,250.1,242.7,235.9
XS GIS Cut Line= 3
     1658683.975      606598.748     1658733.889      606698.574
     1658795.738      606949.225
#Sta/Elev= 30
       0  974.47       4  971.42    15.9  959.98    23.9  953.32    35.9  944.74
    45.8  938.45    49.8  936.65    61.8  933.54    69.8   935.1    85.7  934.62
   113.6  935.41   119.6  932.96   123.5  929.12   125.5  927.53   129.5  926.77
   141.4     927   145.4  928.19   157.3  934.11   163.2  935.16   232.8  936.38
   278.4  938.72   298.3  938.86   302.3  941.31   306.2  946.47   308.2  948.48
   312.2  950.95   328.1  958.25   351.9   971.2   359.8  973.29   369.8  977.27
#Mann= 3 , 0 , 0
       0      .1       0   123.5    .045       0   145.4      .1       0
Bank Sta=123.5,145.4
XS Rating Curve= 0 ,0
Exp/Cntr=0.3,0.1

Type RM Length L Ch R = 1 ,13969.3 ,161.5,165.8,169
XS GIS Cut Line= 4
     1658457.196      606739.807     1658491.918      606772.359
     1658519.045      606813.591      1658605.85      607002.393
#Sta/Elev= 30
       0   967.2       4  966.34     9.9  965.52    15.9  963.92    23.8  960.78
    29.8  957.62    37.7  951.47    39.7  949.47    45.6  941.52    49.6  937.66
    55.5  931.18    59.4  927.67    61.4  926.14    63.4  925.12    65.4  924.78
    81.2  924.83    83.1  925.46    85.1   926.7    87.1  928.33      91  931.36
      93  932.31      97  933.23   176.9  934.08   218.8   933.9   238.8  934.74
   254.8  934.44   256.8  935.02   262.8  939.53   278.8  948.39   304.8  964.92
#Mann= 3 , 0 , 0
       0      .1       0    59.4    .045       0    87.1      .1       0
Bank Sta=59.4,87.1
XS Rating Curve= 0 ,0
Exp/Cntr=0.3,0.1

Type RM Length L Ch R = 1 ,13803.4 ,216,233.3,250.3
XS GIS Cut Line= 4
     1658354.114      606775.614     1658346.519      606836.378
     1658419.218      607014.329      1658436.58      607076.178
#Sta/Elev= 30
       0  954.09     7.9  952.75    17.8  949.77    57.3  935.47    63.2  933.88
    71.2  933.08    73.1  932.56    77.1  930.45      85  924.73    88.8  922.91
    94.9  922.33    96.9  922.38    98.9  923.06   100.9  924.16   103.8  925.06
   112.8  928.54   116.7  929.07   134.6   929.5   152.4   930.7     196  930.66
   227.7  932.45   237.6   932.5   245.5  932.14   247.5  932.45   249.5  933.68
   255.4  938.52   265.2  944.27   286.6  958.17   311.9  972.76   317.7  976.53
#Mann= 3 , 0 , 0
       0     .06       0      85    .045       0   103.8     .06       0
Bank Sta=85,103.8
XS Rating Curve= 0 ,0
Exp/Cntr=0.3,0.1

Type RM Length L Ch R = 1 ,13570.1 ,282,282.6,282.2
XS GIS Cut Line= 4
     1658195.694      606736.551     1658163.142      606887.376
     1658089.357      607084.859      1658055.72      607180.345
#Sta/Elev= 30
       0  953.95    41.5  943.92    73.2  938.32      89  933.04   130.6  930.15
   168.2   928.9   172.2   928.3   180.2   925.2   184.1  924.48   194.1  923.01
     210  922.54     216  920.01   217.9  920.23   223.2  922.95   235.8  927.03
   257.7  927.03   279.6  927.89   295.5  927.56   307.4  930.37   339.3  931.69
   361.1  934.02   371.1  936.65     385  942.85   402.8  953.46   410.8  956.76
   416.7  961.09   428.6  968.78   440.6  975.05   456.4  979.34   466.4   983.4
#Mann= 3 , 0 , 0
       0     .06       0     210    .045       0   223.2     .06       0
Bank Sta=210,223.2
XS Rating Curve= 0 ,0
Exp/Cntr=0.3,0.1

Type RM Length L Ch R = 1 ,13287.5 ,206.2,198.1,190.1
XS GIS Cut Line= 4
     1657959.149      606676.873     1657935.277      606723.531
      1657822.43      607007.819     1657814.835       607100.05
#Sta/Elev= 30
       0  959.89     5.8  953.74    11.6  948.57      33  933.16    48.5  927.34
    56.4  925.44    90.4  924.45   164.4  924.84   208.3  924.12   218.3  921.04
   228.3  919.35   232.3  917.49   234.3  917.38   242.3  917.62   246.3  920.42
   250.3  922.76   252.3  923.18   262.3  923.44   274.3  924.84   292.3  924.86
   308.3  926.12   320.3  925.99   330.3   927.3   364.2   928.3   379.9  935.09
   389.8  937.89   397.7  941.15   415.4  951.74     439  967.49   450.8  974.72
#Mann= 3 , 0 , 0
       0     .06       0   228.3    .045       0   246.3     .06       0
Bank Sta=228.3,246.3
XS Rating Curve= 0 ,0
Exp/Cntr=0.3,0.1

Type RM Length L Ch R = 1 ,13089.5 ,242.2,243,242.8
XS GIS Cut Line= 3
     1657669.435      606636.725     1657681.371       606721.36
     1657671.606      607095.709
#Sta/Elev= 30
       0  986.93    27.8  961.92    41.7  947.49    47.7  941.98    63.6  931.28
    75.5  925.81    89.5  922.81   109.4  921.62   133.3  921.35   179.1  922.19
   181.1  921.62   185.1   918.3     189  915.97     203  915.73     207  916.41
     211  918.33   216.9  920.56   222.9  921.09   260.8   921.3   282.7  922.82
   298.6  922.33   306.6   923.9   360.4  924.42   376.3  925.91   396.2  930.91
   402.2  933.38   408.2  936.55   414.1  940.86   432.1  949.21     460  965.12
#Mann= 3 , 0 , 0
       0      .1       0   185.1    .045       0     211      .1       0
#XS Ineff= 2 , 0
           178.4  922.88  283.02          922.84
Permanent Ineff=
       F       F
Bank Sta=185.1,211
XS Rating Curve= 0 ,0
Exp/Cntr=0.3,0.1

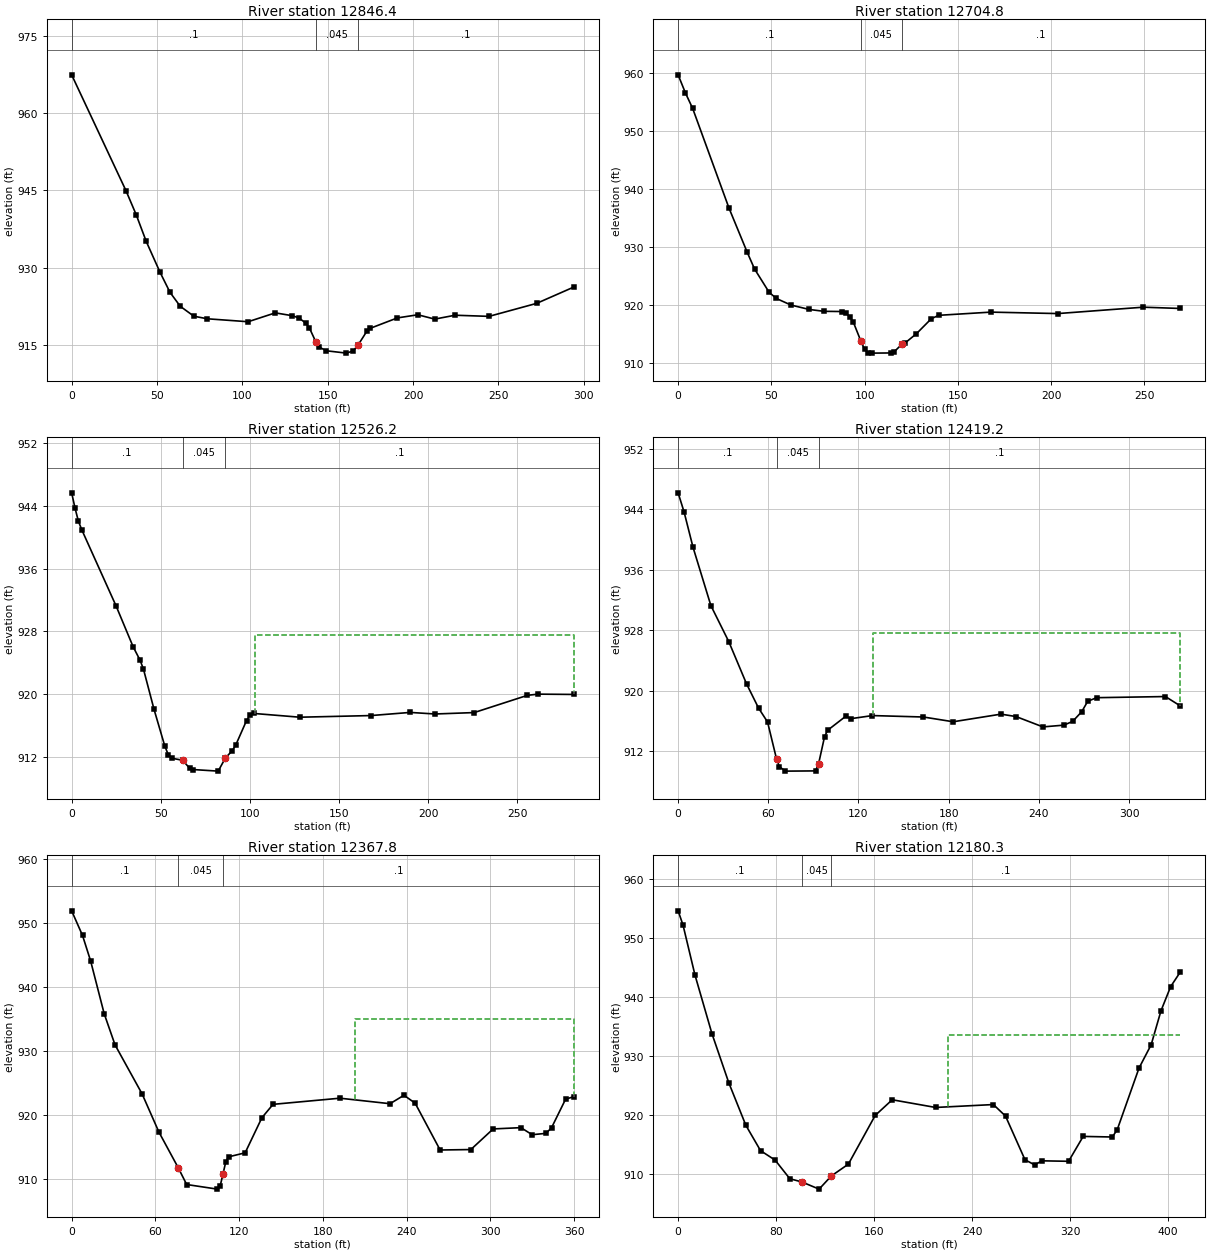
Type RM Length L Ch R = 1 ,12846.4 ,131.4,141.6,150.7
XS GIS Cut Line= 2
     1657442.656      606686.638      1657432.89      606980.692
#Sta/Elev= 30
       0  967.42    31.8  944.97    37.8   940.3    43.7   935.1    51.7  929.18
    57.6  925.24    63.6  922.53    71.6   920.6    79.5   920.1   103.4  919.53
   119.3  921.25   129.2   920.7   133.2  920.27   137.2  919.23   139.2  918.38
   143.1  915.58   145.1  914.61   149.1   913.9     161  913.44     165  913.88
   167.9  915.06     173  917.72   174.9  918.25   190.8  920.27   202.8  920.88
   212.7  920.04   224.6  920.79   244.5  920.57   272.4  923.09   294.2  926.26
#Mann= 3 , 0 , 0
       0      .1       0   143.1    .045       0   167.9      .1       0
Bank Sta=143.1,167.9
XS Rating Curve= 0 ,0
Exp/Cntr=0.3,0.1

Type RM Length L Ch R = 1 ,12704.8 ,180.1,178.6,177
XS GIS Cut Line= 3
     1657352.595      606684.468     1657327.639      606762.593
     1657245.173      606930.779
#Sta/Elev= 30
       0  959.67     3.9  956.56     7.8  953.88    27.3  936.68    37.1  929.04
      41  926.19    48.8  922.18    52.7  921.11    60.5  919.98    70.3  919.22
    78.1   918.9      88  918.86      90  918.59      92  917.97      94     917
      98  913.77     100  912.34   101.9  911.73   103.9  911.69   113.9  911.72
   115.9  911.93   119.9   913.2   121.9  913.49   127.8  915.04   135.8  917.63
   139.8  918.21   167.7  918.76   203.6  918.51   249.4  919.61   269.3  919.39
#Mann= 3 , 0 , 0
       0      .1       0      98    .045       0   119.9      .1       0
Bank Sta=98,119.9
XS Rating Curve= 0 ,0
Exp/Cntr=0.3,0.1

Type RM Length L Ch R = 1 ,12526.2 ,107.9,107,106.1
XS GIS Cut Line= 3
     1657169.218      606660.596     1657159.453      606699.659
     1657068.307      606923.183
#Sta/Elev= 30
       0  945.66     1.9  943.71     3.8  942.03     5.8  940.89    24.9  931.26
    34.5  926.04    38.4  924.32    40.3  923.18    46.2  918.08    52.2  913.43
    54.2  912.29    56.2  911.84    62.2  911.59    66.2  910.57    68.2   910.4
    82.2   910.2    86.2  911.86    90.1  912.81    92.1  913.55    98.1  916.64
   100.1  917.37   102.1  917.55     128  917.07   167.9  917.28   189.9  917.68
   203.8  917.48   225.8  917.66   255.7  919.86   261.7  920.01   281.7  919.97
#Mann= 3 , 0 , 0
       0      .1       0    62.2    .045       0    86.2      .1       0
#XS Ineff= 2 , 0
                          102.83          927.55
Permanent Ineff=
       F       F
Bank Sta=62.2,86.2
XS Rating Curve= 0 ,0
Exp/Cntr=0.3,0.1

Type RM Length L Ch R = 1 ,12419.2 ,49.7,51.4,53.1
XS GIS Cut Line= 4
     1657074.817      606632.385     1657053.116      606676.873
     1657020.564      606766.933     1656954.375        606943.8
#Sta/Elev= 30
       0  946.19       4  943.63     9.9  938.99    21.8  931.25    33.7  926.48
    45.5  920.89    53.5  917.68    59.5  915.83    65.5  910.91    67.4   909.9
    71.4  909.32    91.4  909.35    93.4  910.25    97.4  913.86    99.4  914.72
   111.4  916.57   115.3  916.28   129.3  916.68   163.2  916.49     183  915.86
   214.8  916.87   224.8  916.55   242.7  915.18   256.6  915.41   262.5  915.91
   268.5  917.19   272.5  918.57   278.4  919.05   324.2   919.2   334.1  917.96
#Mann= 3 , 0 , 0
       0      .1       0    65.5    .045       0    93.4      .1       0
#XS Ineff= 2 , 0
                          129.58          927.56
Permanent Ineff=
       F       F
Bank Sta=65.5,93.4
XS Rating Curve= 0 ,0
Exp/Cntr=0.3,0.1

Type RM Length L Ch R = 1 ,12367.8 ,180.7,187.5,193.7
XS GIS Cut Line= 3
      1657034.67      606607.428     1657010.798      606651.916
     1656883.845      606934.034
#Sta/Elev= 30
       0  951.88     7.8  948.03    13.6  944.05    23.3  935.82    31.1  930.94
    50.5  923.28    62.5  917.34    76.4  911.74    82.4  909.14   104.4  908.42
   106.4   908.9   108.4  910.77   110.4  912.65   112.4  913.46   124.3  914.09
   136.3  919.57   144.3  921.66   192.2  922.62   228.1  921.76   238.1  923.08
   246.1  921.84     264  914.53     286   914.6     302  917.82   321.9  918.02
   329.9  916.92   339.9  917.13   343.9  918.04   353.9  922.47   359.8  922.86
#Mann= 3 , 0 , 0
       0      .1       0    76.4    .045       0   108.4      .1       0
#XS Ineff= 2 , 0
                          202.66          935.05
Permanent Ineff=
       F       F
Bank Sta=76.4,108.4
XS Rating Curve= 0 ,0
Exp/Cntr=0.3,0.1

Type RM Length L Ch R = 1 ,12180.3 ,197.8,194.3,190.4
XS GIS Cut Line= 5
     1656891.441      606534.728     1656859.974      606572.706
     1656780.764      606664.937     1656746.041      606744.147
     1656670.087      606876.525
#Sta/Elev= 30
       0  954.58       4  952.17    13.8  943.69    27.6  933.81    41.4  925.47
    55.3  918.29    67.3     914    79.2   912.4    91.2  909.25   101.1   908.7
   115.1  907.49   125.1  909.72     139  911.72   160.9  919.96   174.8  922.61
   210.2  921.31   257.4   921.8   267.3  919.85   283.2  912.46   291.1  911.59
     297  912.28   318.8   912.2   330.7  916.41   354.5  916.31   358.5  917.55
   376.3  927.98   386.2  931.92   394.2  937.65   402.1  941.75     410  944.23
#Mann= 3 , 0 , 0
       0      .1       0   101.1    .045       0   125.1      .1       0
#XS Ineff= 2 , 0
                          220.55           933.6
Permanent Ineff=
       F       F
Bank Sta=101.1,125.1
XS Rating Curve= 0 ,0
Exp/Cntr=0.3,0.1

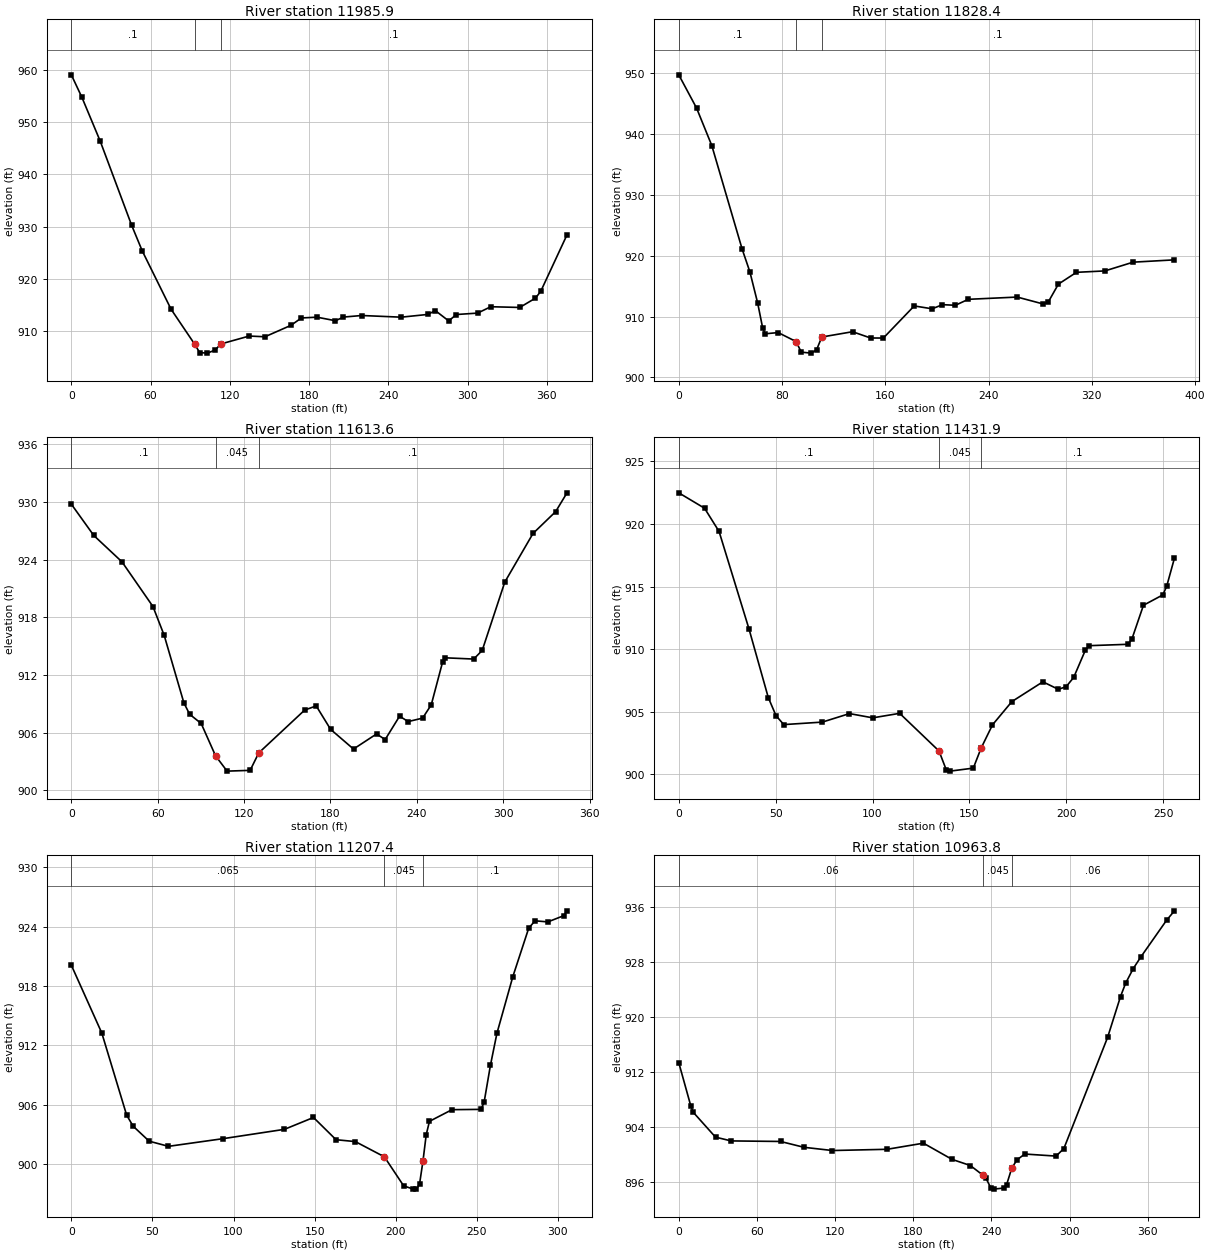
Type RM Length L Ch R = 1 ,11985.9 ,151.4,157.6,163.2
XS GIS Cut Line= 4
     1656709.149      606429.477     1656673.342      606489.156
     1656613.663      606586.812     1656514.922      606750.657
#Sta/Elev= 30
       0  959.06       8  954.76    21.9  946.35    45.7  930.25    53.7  925.36
    75.5  914.21    93.3  907.54    97.2   905.9   103.1   905.8   109.1  906.42
     113  907.54   134.7  909.07   146.6  908.93   166.3  911.12   174.2  912.53
     186  912.68     200     912     206   912.7   219.9     913   249.8  912.68
   269.7   913.2   275.7  913.92   285.7  911.97   291.6  913.19   307.6  913.46
   317.6  914.68   339.5  914.54   351.4  916.32   355.4  917.62   375.3  928.44
#Mann= 3 , 0 , 0
       0      .1       0    93.3    .045       0     113      .1       0
Bank Sta=93.3,113
XS Rating Curve= 0 ,0
Exp/Cntr=0.3,0.1

Type RM Length L Ch R = 1 ,11828.4 ,209.5,214.8,215.8
XS GIS Cut Line= 4
     1656593.047      606349.182      1656568.09      606391.499
     1656466.093      606489.156     1656353.246      606646.491
#Sta/Elev= 30
       0  949.75    13.8  944.28    25.6  938.11    49.1  921.09    55.1  917.34
    61.1  912.24      65  908.11      67  907.16      77  907.36    90.9  905.88
    94.9  904.14   102.8  903.98   106.8  904.54   110.8  906.63   134.6   907.5
   148.6  906.47   158.5  906.46   182.4  911.74   196.3  911.27   204.3  911.95
   214.3  911.85   224.3  912.83   262.2   913.2   282.2  912.07   286.2  912.37
   294.1  915.33   308.1  917.27   330.1   917.5     352  918.94     384  919.32
#Mann= 3 , 0 , 0
       0      .1       0    90.9    .045       0   110.8      .1       0
Bank Sta=90.9,110.8
XS Rating Curve= 0 ,0
Exp/Cntr=0.3,0.1

Type RM Length L Ch R = 1 ,11613.6 ,184.6,181.7,181.5
XS GIS Cut Line= 4
     1656420.521      606236.334     1656386.883      606302.524
     1656254.505      606424.051     1656183.975      606480.475
#Sta/Elev= 30
       0  929.78    15.6  926.52    35.2  923.77    56.7  919.12    64.5  916.12
    78.2  909.08    82.2   907.9    90.2  906.94   100.2  903.57   108.2  901.98
   124.2  902.06   130.2  903.88   162.1  908.34   170.1  908.77   180.1  906.33
     196  904.28     212  905.85     218  905.27     228   907.7     234  907.14
     244   907.5     250  908.88   257.9  913.35   259.8  913.78   279.5  913.65
   285.4  914.55   301.1  921.67   320.7  926.73   336.4     929   344.3  930.96
#Mann= 3 , 0 , 0
       0      .1       0   100.2    .045       0   130.2      .1       0
Bank Sta=100.2,130.2
XS Rating Curve= 0 ,0
Exp/Cntr=0.3,0.1

Type RM Length L Ch R = 1 ,11431.9 ,221.9,224.5,226.4
XS GIS Cut Line= 3
     1656305.503      606177.741     1656278.376      606195.102
      1656105.85      606337.246
#Sta/Elev= 30
       0  922.49    13.3  921.26    20.8   919.4    36.2  911.63    46.2  906.12
    50.2  904.67    54.2  903.96    74.1  904.16    88.1  904.84   100.1   904.5
     114  904.86   134.3  901.85     138  900.36     140  900.24     152  900.48
     156  902.07   161.9  903.94   171.9   905.8   187.9  907.38   195.9  906.78
   199.9  906.99   203.8  907.73   209.8   909.9   211.8  910.27   231.8  910.38
   233.8  910.78   239.8   913.5   249.8  914.33   251.8  915.02   255.8  917.27
#Mann= 3 , 0 , 0
       0      .1       0   134.3    .045       0     156      .1       0
Bank Sta=134.3,156
XS Rating Curve= 0 ,0
Exp/Cntr=0.3,0.1

Type RM Length L Ch R = 1 ,11207.4 ,242.6,243.6,245
XS GIS Cut Line= 4
     1656194.826      606052.958     1656168.784      606068.149
     1655985.408      606194.017     1655946.345      606229.824
#Sta/Elev= 30
       0   920.1    18.8  913.23    34.1  904.93    38.1  903.81      48  902.29
    59.9  901.77    93.7  902.55   131.4  903.49   149.3  904.69   163.2  902.44
   175.1  902.25     193  900.71   204.9  897.77   210.9  897.44   212.8  897.44
   214.7  897.97   216.8  900.28   218.8  902.95   220.8   904.3   234.7  905.48
   252.6  905.51   254.5  906.24   258.4  909.98   262.4  913.21   272.2  918.94
     282  923.85   285.9  924.59   293.8  924.48   303.6  925.11   305.6   925.6
#Mann= 3 , 0 , 0
       0    .065       0     193    .045       0   216.8      .1       0
Bank Sta=193,216.8
XS Rating Curve= 0 ,0
Exp/Cntr=0.3,0.1

Type RM Length L Ch R = 1 ,10963.8 ,102.8,105.1,107.4
XS GIS Cut Line= 4
     1656049.427      605871.751     1656034.236      605888.027
     1655790.095      606035.596     1655731.501      606078.999
#Sta/Elev= 30
       0   913.4     9.3  907.05    11.1  906.17    28.2  902.55    40.2     902
    78.1  901.92    96.1  901.07     118   900.6   159.9  900.78   187.8  901.67
   209.8  899.31   223.8  898.42   233.7  896.98   235.8  896.57   239.7  895.11
   241.7  894.98   249.7  895.14   251.7  895.65   255.7  898.08   259.7  899.25
   265.6  900.09   289.6  899.79   295.6  900.88   329.2  917.08   339.1  923.02
     343  924.95   348.9   927.1   354.8  928.81   374.5  934.14   380.5   935.5
#Mann= 3 , 0 , 0
       0     .06       0   233.7    .045       0   255.7     .06       0
Bank Sta=233.7,255.7
XS Rating Curve= 0 ,0
Exp/Cntr=0.3,0.1

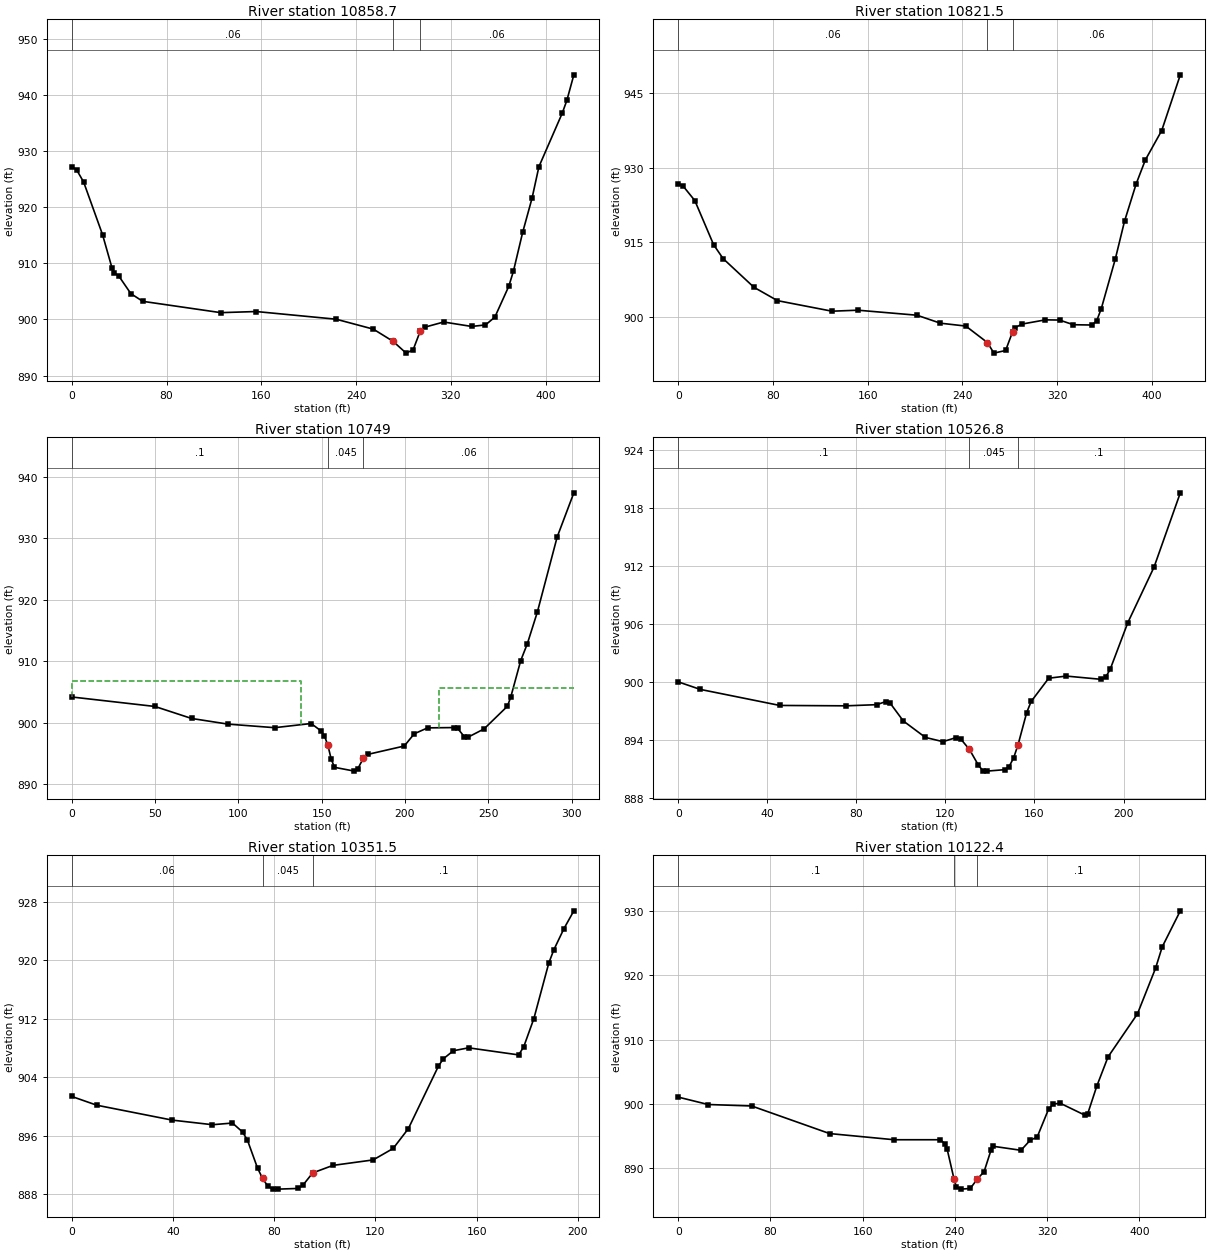
Type RM Length L Ch R = 1 ,10858.7 ,37.1,37.1,37.1
XS GIS Cut Line= 5
     1656046.172      605830.518     1655848.689      605894.537
     1655812.882      605904.303     1655741.267       605937.94
     1655650.121      605979.173
#Sta/Elev= 30
       0  927.26       4  926.72      10  924.53      26  915.12    33.9  909.24
    35.9  908.36    39.9  907.69    49.9  904.61    59.9  903.24   125.8  901.22
   155.7  901.42   223.2  900.05   254.6  898.28   271.3   896.1   282.3     894
   288.2  894.59   294.2  897.91   298.1  898.63     314  899.55   337.6  898.76
   349.3  899.03   357.2  900.42     369  905.94   372.9  908.62   380.7  915.55
   388.6  921.63   394.4  927.25   414.1   936.8     418  939.08   423.9  943.64
#Mann= 3 , 0 , 0
       0     .06       0   271.3    .045       0   294.2     .06       0
Bank Sta=271.3,294.2
XS Rating Curve= 0 ,0
Exp/Cntr=0.3,0.1

Type RM Length L Ch R = 1 ,10821.5 ,72.2,72.5,72
XS GIS Cut Line= 5
     1656019.045      605802.307     1655821.562      605866.326
     1655785.755      605876.091      1655714.14      605909.728
     1655622.994      605950.961
#Sta/Elev= 30
       0  926.77       4  926.31      14  923.36    29.9  914.47    37.9  911.69
    63.9  905.93    83.8  903.24   129.8  901.12   151.7  901.32   201.6  900.31
   221.3  898.71   242.8  898.13   261.1   894.8   266.5  892.69   276.4  893.22
   282.3  896.98   284.3  897.79   290.2  898.53     310  899.38   321.9  899.34
   333.6   898.4   349.3  898.34   353.3  899.19   357.2  901.65     369   911.6
   376.8  919.21   386.6   926.7   394.4  931.54   408.2  937.44   423.9  948.64
#Mann= 3 , 0 , 0
       0     .06       0   261.1    .045       0   282.3     .06       0
Bank Sta=261.1,282.3
XS Rating Curve= 0 ,0
Exp/Cntr=0.3,0.1

Type RM Length L Ch R = 1 ,10749   ,214.6,222.2,229.1
XS GIS Cut Line= 3
     1655877.986      605751.308     1655641.441      605867.411
     1655606.718      605882.602
#Sta/Elev= 30
       0   904.2    49.9  902.66    71.9  900.71    93.8  899.79   121.8  899.21
   143.7  899.89   149.7  898.67   151.7  897.85   153.7   896.4   155.7  894.13
   157.7  892.77   169.7  892.15   171.7  892.52     175  894.24   177.7  894.87
   199.6  896.23   205.6  898.22   213.6  899.18   229.6  899.23   231.6   899.1
   235.6  897.77   237.6  897.63   247.5  899.01   261.5  902.69   263.5  904.16
   269.5  910.11   273.5  912.87   279.5  918.01   291.4  930.21   301.4  937.38
#Mann= 3 , 0 , 0
       0      .1       0   153.7    .045       0     175     .06       0
#XS Ineff= 2 , 0
          137.33  906.77  220.73          905.62
Permanent Ineff=
       F       F
Bank Sta=153.7,175
XS Rating Curve= 0 ,0
Exp/Cntr=0.3,0.1

Type RM Length L Ch R = 1 ,10526.8 ,188.7,175.4,161.7
XS GIS Cut Line= 4
     1655775.989      605606.994     1655684.843      605626.525
     1655612.144      605635.206      1655553.55      605642.801
#Sta/Elev= 30
       0  899.98     9.9   899.2    45.6  897.54    75.4   897.5    89.2  897.62
    93.2  897.94    95.2  897.77   101.1  895.93     111  894.23   118.9  893.79
   124.9  894.22   126.8  894.09   130.8  892.98   134.8  891.36   136.8  890.79
   138.6  890.74   146.6  890.89   148.6  891.21   150.6  892.09   152.6  893.45
   156.5   896.8   158.5  897.95   166.4  900.36   174.3  900.58   190.1  900.24
     192  900.48     194  901.28   201.9   906.1   213.7  911.86   225.5  919.55
#Mann= 3 , 0 , 0
       0      .1       0   130.8    .045       0   152.6      .1       0
Bank Sta=130.8,152.6
XS Rating Curve= 0 ,0
Exp/Cntr=0.3,0.1

Type RM Length L Ch R = 1 ,10351.5 ,235.2,229.1,222.1
XS GIS Cut Line= 2
     1655679.418      605404.086     1655529.679      605534.294
#Sta/Elev= 30
       0  901.37     9.9  900.17    39.7  898.13    55.6   897.5    63.5  897.73
    67.5   896.5    69.4   895.4    73.4  891.57    75.4  890.14    77.4  889.12
    79.4  888.69    81.4  888.68    89.3  888.77    91.3   889.2    95.2   890.9
   103.2  891.93   119.1  892.68     127  894.25     133  896.96   144.9  905.53
   146.8  906.52   150.8  907.63   156.8  908.03   176.6  907.06   178.6  908.18
   182.6  912.03   188.5  919.64   190.5  921.46   194.5  924.36   198.4  926.79
#Mann= 3 , 0 , 0
       0     .06       0    75.4    .045       0    95.2      .1       0
Bank Sta=75.4,95.2
XS Rating Curve= 0 ,0
Exp/Cntr=0.3,0.1

Type RM Length L Ch R = 1 ,10122.4 ,141.6,137.4,132.9
XS GIS Cut Line= 4
     1655603.463      605161.031     1655500.382       605225.05
     1655379.939      605413.852     1655351.727      605499.572
#Sta/Elev= 30
       0  901.05    25.9   899.9    63.7  899.67   131.3  895.38   187.3  894.42
   227.3  894.42   231.3  893.79   233.3  892.92   239.3  888.25   241.3  887.07
   245.3  886.74   253.3  886.84   259.3  888.28   265.3  889.46   271.3   892.8
   273.3   893.4   297.3  892.78   305.3  894.35   311.3  894.82   321.3  899.21
   325.3  899.97   331.3   900.1   353.1  898.21   355.1  898.42     363  902.73
   372.8   907.3   398.3  913.99     414  921.08   419.8  924.41   435.5  930.02
#Mann= 3 , 0 , 0
       0      .1       0   239.3    .045       0   259.3      .1       0
Bank Sta=239.3,259.3
XS Rating Curve= 0 ,0
Exp/Cntr=0.3,0.1