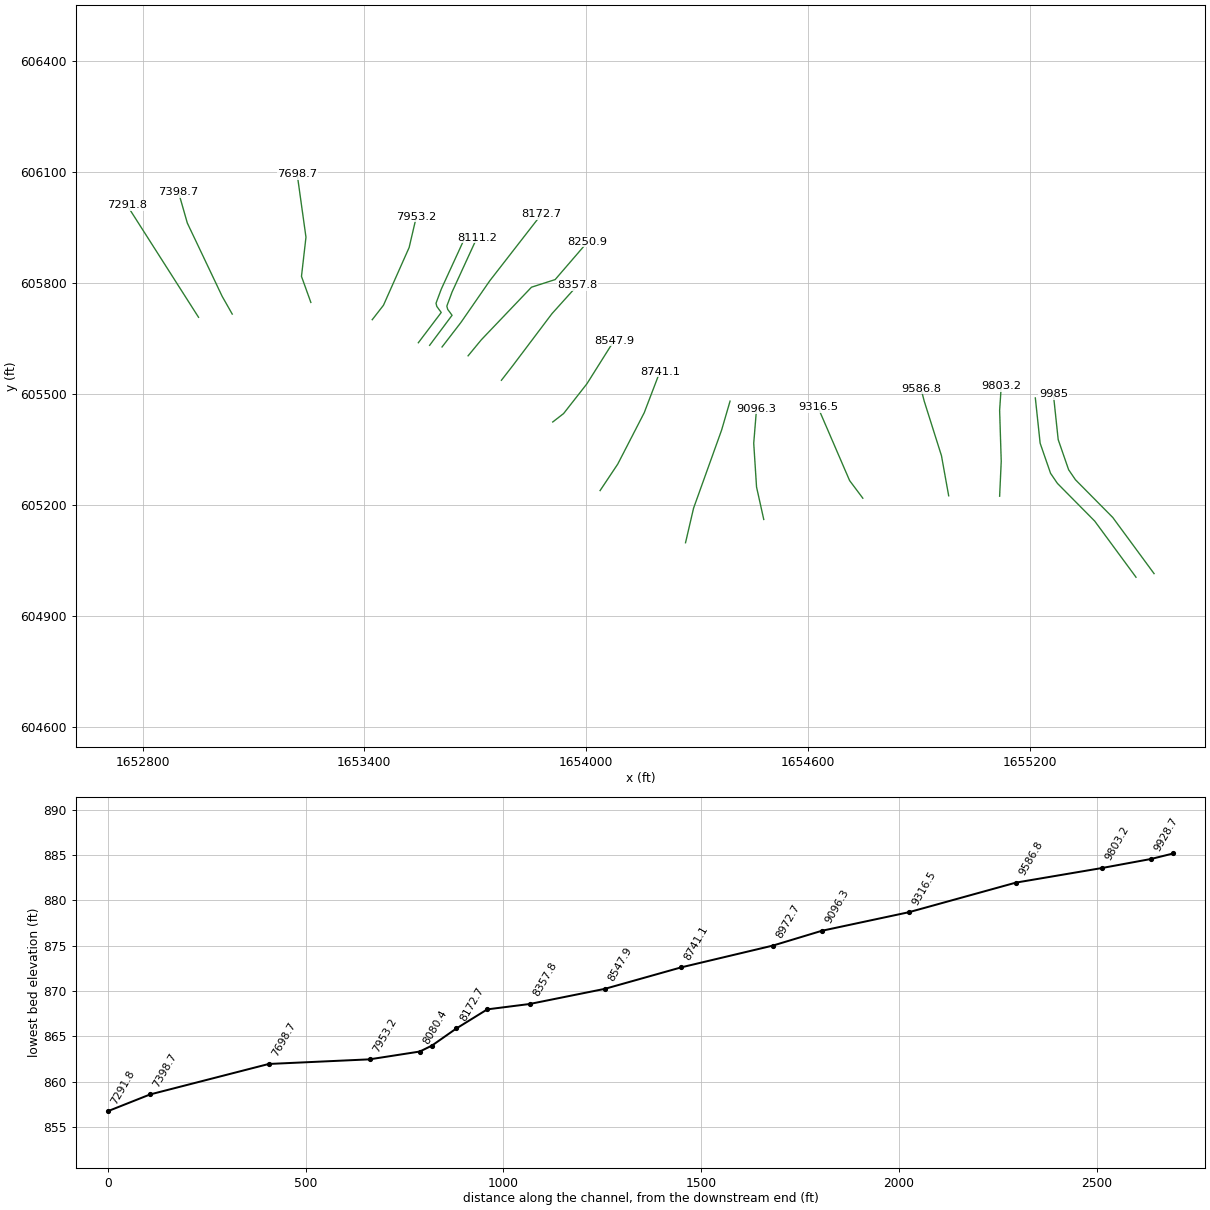
HEC-RAS study NFSHORTCRK.prj: NFSHORTCRK

--- NFSHORTCRK.g01 (geometry) --- (continued)

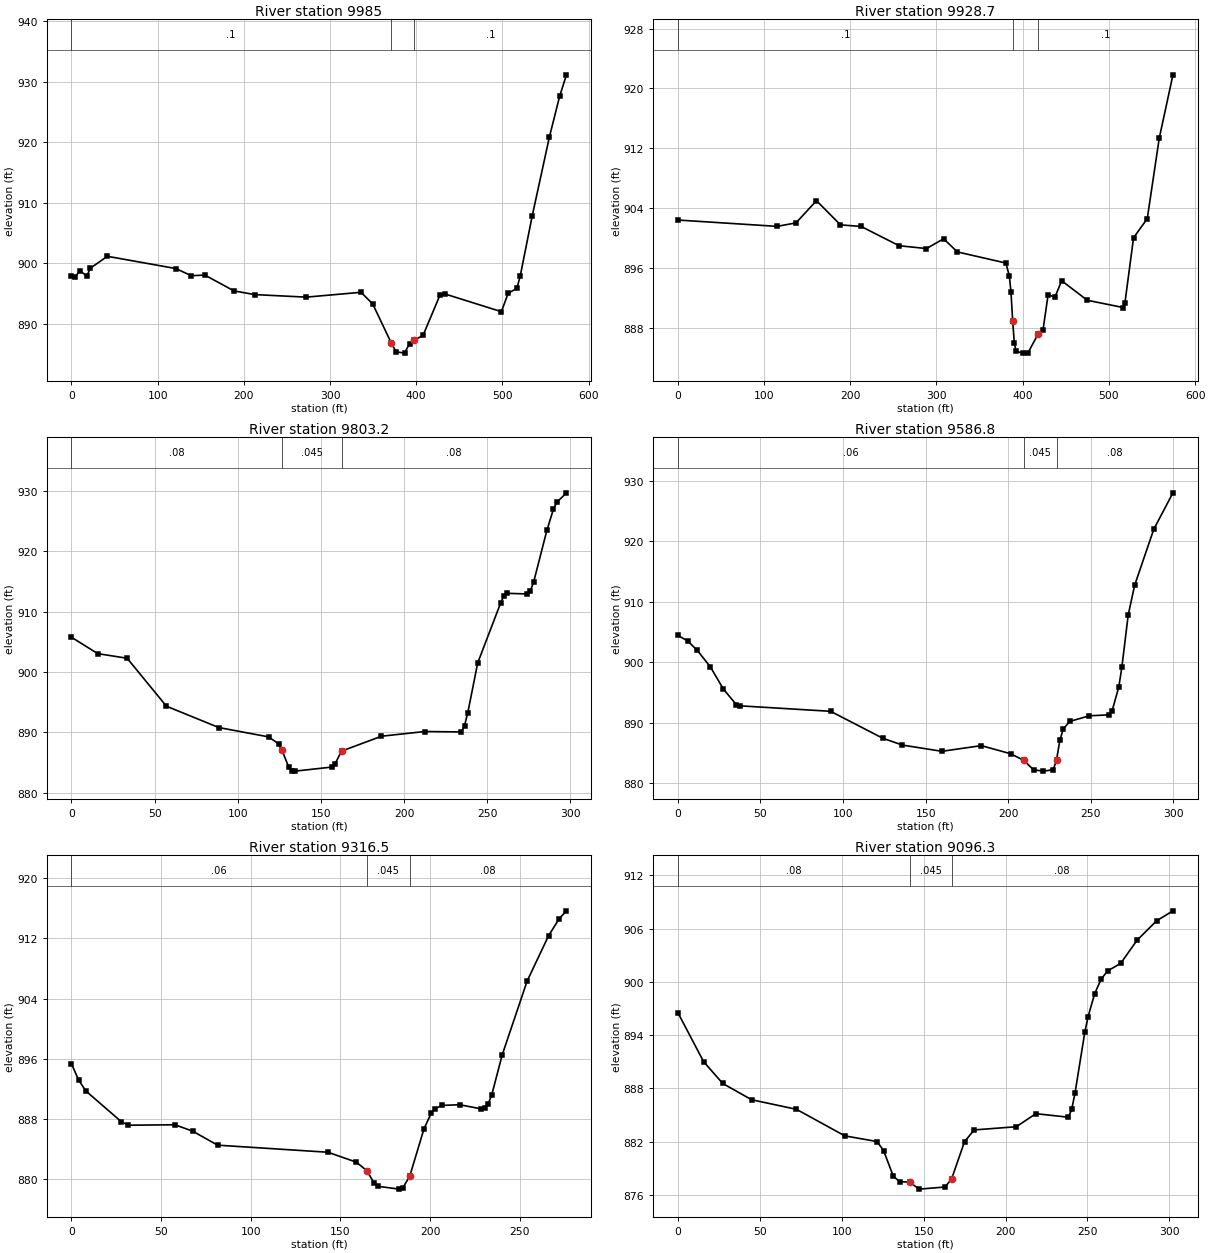
Type RM Length L Ch R = 1 ,9985    ,55.5,56.3,56.7
XS GIS Cut Line= 6
     1655536.189      605014.546     1655424.427      605166.456
     1655323.515      605268.452     1655305.069      605295.579
     1655276.857      605376.959     1655263.837      605499.572
#Sta/Elev= 30
       0  897.99       4  897.71     9.9  898.79    17.9  897.89    21.8  899.18
    41.7  901.16   121.1  899.14     139  897.96   154.8  898.06   188.6  895.45
   212.6  894.84   272.5  894.42     336  895.22   349.5   893.3   370.8  886.93
   376.6  885.41   386.4  885.18   392.3  886.75   397.9  887.34   407.9   888.1
   427.5  894.74   433.4  894.94   498.8  892.02   506.7  895.08   516.7  895.85
   520.6  897.88   534.6  907.86   554.4   920.8   566.4   927.6   574.3  931.11
#Mann= 3 , 0 , 0
       0      .1       0   370.8    .045       0   397.9      .1       0
Bank Sta=370.8,397.9
XS Rating Curve= 0 ,0
Exp/Cntr=0.3,0.1

Type RM Length L Ch R = 1 ,9928.7  ,133.6,125.5,118.4
XS GIS Cut Line= 6
     1655487.361      605004.781     1655375.599       605156.69
     1655274.687      605258.687     1655256.241      605285.814
     1655228.029      605367.194     1655215.008      605489.807
#Sta/Elev= 30
       0  902.39   115.1  901.54     137  902.01   160.8  904.98   188.6  901.74
   212.6  901.53   256.6  898.95   288.4  898.57   308.3  899.88   324.2  898.12
   380.5  896.63   384.5   894.9   386.4  892.76   388.4  888.84   390.3   885.9
   392.3  884.82   400.1  884.57     406  884.59   417.9  887.13   423.6  887.69
   429.5  892.41   437.3  892.04   445.2  894.26   474.9  891.65   516.7  890.67
   518.6   891.3   528.6  900.02   544.5  902.57   558.4  913.34   574.3  921.83
#Mann= 3 , 0 , 0
       0      .1       0   388.4    .045       0   417.9      .1       0
Bank Sta=388.4,417.9
XS Rating Curve= 0 ,0
Exp/Cntr=0.3,0.1

Type RM Length L Ch R = 1 ,9803.2  ,209.3,216.4,220.3
XS GIS Cut Line= 4
     1655118.437      605223.965     1655122.777      605318.366
     1655118.437      605456.169     1655122.777      605521.274
#Sta/Elev= 30
       0  905.77    15.8  903.05    33.5  902.28    57.1  894.33    88.6  890.79
   118.5  889.24   124.5   888.1   126.5  887.08   130.5  884.32   132.5   883.6
   134.5  883.56   156.4  884.23   158.4  884.73   162.4  886.88   186.4  889.35
   212.4  890.13   234.4  890.06   236.3   891.1   238.3  893.27   244.2  901.48
   258.1   911.5     260  912.66     262  913.05   273.9  912.95   275.9  913.48
   277.8  914.85   285.8  923.48   289.7  926.97   291.7  928.13   297.6  929.72
#Mann= 3 , 0 , 0
       0     .08       0   126.5    .045       0   162.4     .08       0
Bank Sta=126.5,162.4
XS Rating Curve= 0 ,0
Exp/Cntr=0.3,0.1

Type RM Length L Ch R = 1 ,9586.8  ,267.8,270.3,272.3
XS GIS Cut Line= 4
     1654980.633       605225.05     1654961.102      605333.557
     1654914.444      605481.126     1654905.764      605514.763
#Sta/Elev= 30
       0  904.42     5.9  903.51    11.8  901.93    19.7   899.2    27.6  895.52
    35.4  892.97    37.4  892.77    92.5  891.86   124.1   887.4     136  886.27
   159.9  885.24   183.7  886.18   201.5  884.84   209.5  883.73   215.4  882.17
   221.4  881.96   227.3  882.19   229.3  883.82   231.3  887.03   233.3  888.88
   237.2  890.18   249.2  891.12     261  891.27     263  891.99     267  895.87
   268.9  899.24   272.7  907.79   276.6  912.72   288.2  921.99   299.8  928.02
#Mann= 3 , 0 , 0
       0     .06       0   209.5    .045       0   229.3     .08       0
Bank Sta=209.5,229.3
XS Rating Curve= 0 ,0
Exp/Cntr=0.3,0.1

Type RM Length L Ch R = 1 ,9316.5  ,227.5,220.2,211.9
XS GIS Cut Line= 3
     1654748.429      605218.539     1654712.621      605266.282
     1654626.901       605464.85
#Sta/Elev= 30
       0  895.37       4   893.2       8  891.75    27.8  887.66    31.8  887.19
    57.7  887.25    67.6   886.4    81.5  884.54     143   883.6   158.9  882.28
   164.8  881.12   168.7  879.52   170.8  879.08   182.7   878.7   184.7  878.85
   188.6  880.41   196.6  886.74   200.6  888.79   202.5  889.34   206.5  889.82
   216.4  889.91   228.3  889.37   230.3  889.42   232.3  890.01   234.3  891.18
   240.2  896.56   254.1  906.36     266  912.35     272  914.65     276  915.67
#Mann= 3 , 0 , 0
       0     .06       0   164.8    .045       0   188.6     .08       0
Bank Sta=164.8,188.6
XS Rating Curve= 0 ,0
Exp/Cntr=0.3,0.1

Type RM Length L Ch R = 1 ,9096.3  ,132.4,123.6,113.5
XS GIS Cut Line= 4
     1654480.416      605161.031     1654460.885      605248.921
      1654453.29      605367.194     1654460.885       605460.51
#Sta/Elev= 30
       0  896.53    15.7  891.01    27.4  888.55      45  886.72    72.4  885.64
   101.9  882.65   121.6  882.01   125.6  880.98   131.5   878.1   135.5  877.48
   141.4  877.45   147.3  876.65   163.1  876.89   167.1  877.81     175  882.01
   180.9  883.32   206.6  883.68   218.5  885.15   238.4  884.75   240.4  885.64
   242.4  887.45   248.4  894.33   250.4  896.08   254.4  898.66   258.4  900.31
   262.3  901.23   270.3  902.08   280.3  904.69   292.2  906.87   302.2     908
#Mann= 3 , 0 , 0
       0     .08       0   141.4    .045       0   167.1     .08       0
Bank Sta=141.4,167.1
XS Rating Curve= 0 ,0
Exp/Cntr=0.3,0.1

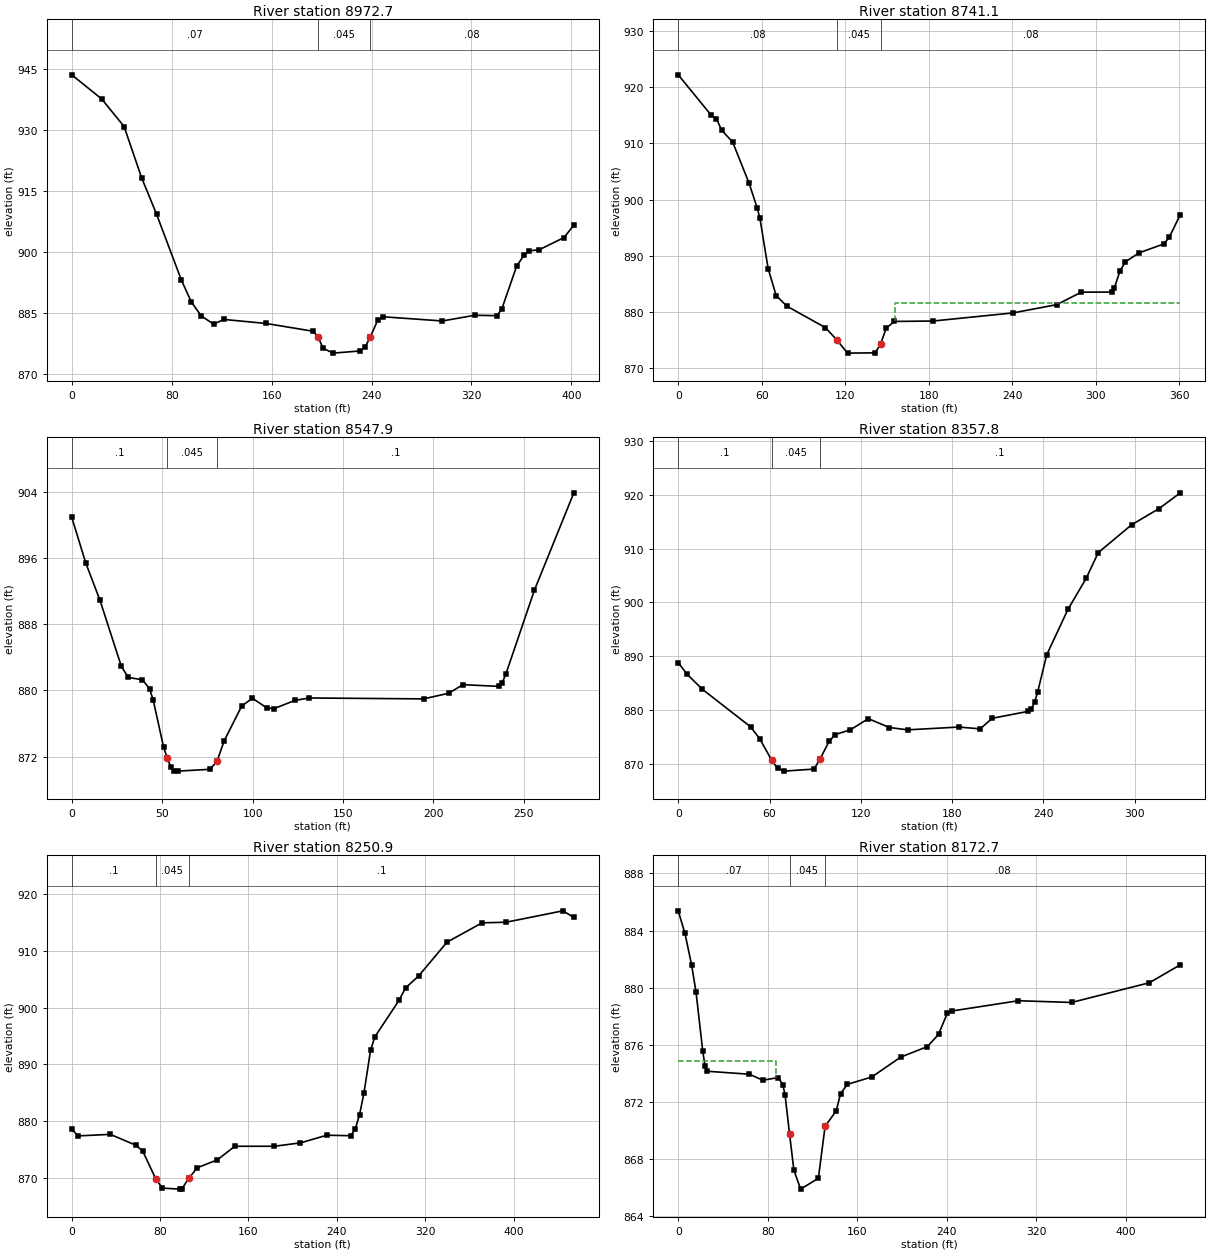
Type RM Length L Ch R = 1 ,8972.7  ,234.5,231.6,229
XS GIS Cut Line= 4
     1654268.828      605098.096     1654290.529      605191.412
     1654366.484      605403.001     1654389.271      605481.126
#Sta/Elev= 30
       0  943.49      24  937.54    41.9  930.77    55.9  918.18    67.9  909.19
    87.8  892.96    95.8  887.58   103.8  884.13   113.7  882.14   121.7  883.31
   155.5  882.32   193.3   880.4   197.3  878.94   201.2  876.22   209.2  875.02
   231.1  875.56   235.1  876.62     239     879     245  883.14     249  883.97
   296.7  882.93   322.6  884.33   340.5  884.23   344.4  885.96   356.3  896.51
   362.3  899.16   366.3  900.19   374.2  900.44   394.1  903.45     402   906.5
#Mann= 3 , 0 , 0
       0     .07       0   197.3    .045       0     239     .08       0
Bank Sta=197.3,239
XS Rating Curve= 0 ,0
Exp/Cntr=0.3,0.1

Type RM Length L Ch R = 1 ,8741.1  ,197.3,193.2,188.8
XS GIS Cut Line= 4
     1654037.708      605239.156     1654085.451       605310.77
     1654157.066      605449.659     1654199.383      605560.336
#Sta/Elev= 30
       0  922.22    23.5  915.08    27.4   914.4    31.3  912.32    39.1  910.24
    50.9  902.91    56.7  898.52    58.7  896.64    64.6   887.7    70.4  882.86
    78.2  880.97   105.8  877.16   113.8  875.01   121.7  872.62   141.5  872.67
   145.4  874.23   149.4  877.05   155.3  878.27     183  878.34   240.4  879.78
     272  881.26   289.7  883.49   311.5   883.5   313.4  884.25   317.4  887.22
   321.3  888.89   331.2  890.49     349  892.09   352.9  893.28   360.8  897.32
#Mann= 3 , 0 , 0
       0     .08       0   113.8    .045       0   145.4     .08       0
#XS Ineff= 2 , 0
                          155.45          881.58
Permanent Ineff=
       F       F
Bank Sta=113.8,145.4
XS Rating Curve= 0 ,0
Exp/Cntr=0.3,0.1

Type RM Length L Ch R = 1 ,8547.9  ,189.5,190.1,190.4
XS GIS Cut Line= 4
      1653909.67      605424.702     1653938.967      605447.489
     1654001.901      605527.784     1654075.685      605644.971
#Sta/Elev= 30
       0  900.91     7.8  895.36    15.6  890.89    27.4  882.92    31.2  881.58
    39.1  881.28      43  880.21      45  878.86    50.8  873.12    52.8  871.84
    54.8  870.73    56.7  870.26    58.7  870.25    76.4  870.47    80.3  871.43
    84.2  873.88      94  878.13    99.9  879.05   107.7  877.91   111.7  877.79
   123.4   878.8   131.3  879.09   194.5  878.98   208.4  879.66   216.3   880.7
   236.1  880.49     238  880.95     240  881.97   255.8  892.12   277.6  903.88
#Mann= 3 , 0 , 0
       0      .1       0    52.8    .045       0    80.3      .1       0
Bank Sta=52.8,80.3
XS Rating Curve= 0 ,0
Exp/Cntr=0.3,0.1

Type RM Length L Ch R = 1 ,8357.8  ,109.4,106.9,104.1
XS GIS Cut Line= 4
     1653770.781       605537.55     1653801.163      605576.612
       1653907.5      605717.671     1653976.944      605794.711
#Sta/Elev= 30
       0  888.78     5.9   886.6    15.8  883.84    47.5  876.84    53.5  874.64
    61.4  870.61    65.4  869.08    69.3  868.58    89.2  868.96    93.2  870.85
    99.1   874.1   103.1  875.39     113  876.26   124.9  878.35   138.8   876.7
   150.7  876.27   184.5  876.79   198.4  876.45   206.3  878.42   230.1  879.72
   232.1  880.21   234.1   881.4   236.1  883.23   242.1  890.23   256.1  898.72
     268  904.46     276  909.28   297.9  914.46   315.9  917.47   329.9  920.41
#Mann= 3 , 0 , 0
       0      .1       0    61.4    .045       0    93.2      .1       0
Bank Sta=61.4,93.2
XS Rating Curve= 0 ,0
Exp/Cntr=0.3,0.1

Type RM Length L Ch R = 1 ,8250.9  ,74.7,78.3,81.8
XS GIS Cut Line= 5
      1653680.72      605603.739     1653716.527      605647.142
     1653852.161      605789.286      1653916.18      605809.902
     1654004.071      605911.899
#Sta/Elev= 30
       0  878.53     5.8  877.38    34.9  877.65    58.2  875.72    64.2  874.71
    76.1  869.78    82.1  868.17    97.9  867.99    99.8  868.06   105.9   869.9
   113.8  871.78   131.7  873.14   147.6  875.55   183.3  875.55   207.1  876.15
   230.9   877.5   252.7  877.41   256.7   878.6   260.6  881.15   264.6  884.98
   270.5  892.46   274.5  894.88   296.3  901.28   302.2  903.47   314.1   905.6
   339.8  911.56   371.5  914.96   393.3  915.07   444.7  917.08   454.6  915.91
#Mann= 3 , 0 , 0
       0      .1       0    76.1    .045       0   105.9      .1       0
Bank Sta=76.1,105.9
XS Rating Curve= 0 ,0
Exp/Cntr=0.3,0.1

Type RM Length L Ch R = 1 ,8172.7  ,52.1,61.5,66.8
XS GIS Cut Line= 4
     1653610.191       605627.61     1653661.189        605693.8
     1653739.314      605806.647     1653879.288      605986.768
#Sta/Elev= 30
       0  885.38       6   883.8    11.9  881.61    15.9   879.7    21.9  875.56
    23.9  874.52    25.9  874.14    63.7  873.93    75.6  873.51    89.5   873.7
    93.5  873.18    95.5   872.5    99.5  869.75   103.4  867.21   109.4  865.88
   125.3  866.64   131.3  870.28   141.2  871.36   145.2  872.58   151.2  873.22
   173.1  873.74   198.9  875.13   222.8  875.87   232.7  876.72   240.6  878.21
   244.6  878.36   304.1  879.08   351.7  878.96   421.2  880.34   448.9   881.6
#Mann= 3 , 0 , 0
       0     .07       0    99.5    .045       0   131.3     .08       0
#XS Ineff= 2 , 0
           87.77  874.88
Permanent Ineff=
       F       F
Bank Sta=99.5,131.3
XS Rating Curve= 0 ,0
Exp/Cntr=0.3,0.1

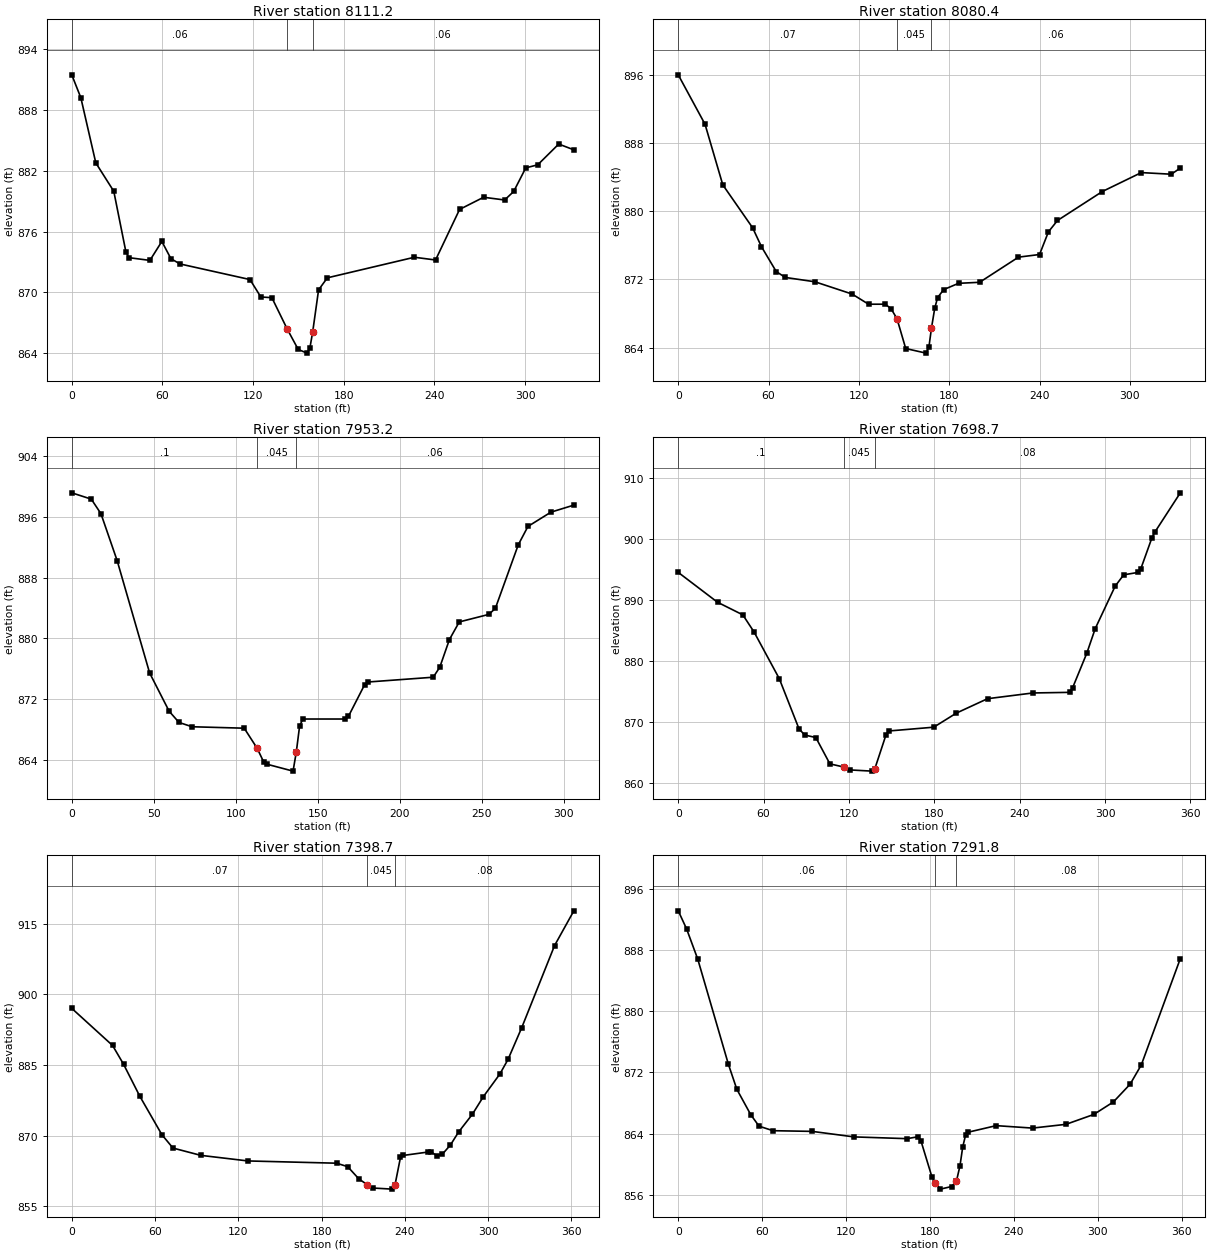
Type RM Length L Ch R = 1 ,8111.2  ,34.2,30.8,30.1
XS GIS Cut Line= 6
     1653576.649      605632.124     1653637.317      605713.331
     1653625.382      605729.607     1653623.212      605738.287
     1653637.317      605776.265     1653704.592      605922.749
#Sta/Elev= 30
       0  891.46       6   889.2    15.9  882.77    27.8  879.97    35.8     874
    37.8  873.42    51.7  873.15    59.6  875.02    65.6  873.32    71.6   872.8
   117.9  871.26   125.1  869.54   132.4  869.47   142.5  866.39   149.8  864.37
   155.6     864   157.5  864.46   159.4  866.09   163.3  870.24   169.1  871.43
   226.7  873.46   240.7  873.19   256.6  878.18   272.5  879.38   286.4  879.11
   292.4  879.95   300.4  882.28   308.3  882.58   322.2  884.63   332.2  884.06
#Mann= 3 , 0 , 0
       0     .06       0   142.5    .045       0   159.4     .06       0
Bank Sta=142.5,159.4
XS Rating Curve= 0 ,0
Exp/Cntr=0.3,0.1

Type RM Length L Ch R = 1 ,8080.4  ,128.5,127.1,126.3
XS GIS Cut Line= 6
     1653546.093      605639.069     1653608.021      605720.926
     1653596.085      605737.202     1653593.915      605745.883
     1653608.021       605783.86     1653675.295      605930.345
#Sta/Elev= 30
       0  895.99    17.8  890.19    29.6  883.08    49.4  878.05    55.3  875.82
    65.1  872.91    71.1  872.22    90.8  871.71   115.5  870.27   126.4  869.08
   137.6  869.08   141.4  868.54   145.3  867.38   151.1  863.88   164.6  863.34
   166.5  864.04   168.2  866.27   170.4  868.63   172.3  869.86   176.3  870.79
   186.2  871.53   200.2  871.65     226   874.6     240  874.91   245.9  877.57
   251.9   878.9   281.7   882.3   307.6  884.52   327.5  884.33   333.5  885.05
#Mann= 3 , 0 , 0
       0     .07       0   145.3    .045       0   168.2     .06       0
Bank Sta=145.3,168.2
XS Rating Curve= 0 ,0
Exp/Cntr=0.3,0.1

Type RM Length L Ch R = 1 ,7953.2  ,247.4,254.6,261.2
XS GIS Cut Line= 4
     1653421.389      605701.395     1653451.771      605740.458
     1653521.215      605896.708     1653540.746      605980.258
#Sta/Elev= 30
       0  899.17    11.9  898.34    17.8  896.42    27.7  890.22    47.5  875.42
    59.4  870.38    65.4   868.9    73.4  868.33   105.2  868.14   113.1  865.49
   117.1  863.68   119.1  863.39     135  862.48     137  865.03     139  868.44
     141  869.35   166.8  869.35   168.8  869.71   178.7  873.89   180.7  874.23
   220.5  874.86   224.5  876.17   230.4  879.83   236.4  882.15   254.4  883.14
   258.4  883.93   272.4  892.32   278.3  894.74   292.3  896.62   306.3  897.55
#Mann= 3 , 0 , 0
       0      .1       0   113.1    .045       0     137     .06       0
Bank Sta=113.1,137
XS Rating Curve= 0 ,0
Exp/Cntr=0.3,0.1

Type RM Length L Ch R = 1 ,7698.7  ,286.3,300,312.5
XS GIS Cut Line= 4
     1653255.373      605748.053     1653229.982      605818.583
     1653242.135      605924.485     1653218.481       606094.19
#Sta/Elev= 30
       0  894.54    27.6  889.65    45.4  887.58    53.3  884.77      71  877.14
    84.8  868.95    88.8  867.89    96.7  867.48   106.6  863.16   116.4  862.64
   120.4  862.17   136.2  861.97   138.1   862.3     146  867.89     148  868.55
   179.6  869.17   195.5  871.48   217.4  873.84   249.3  874.78   275.2  874.88
   277.2  875.63   287.2  881.31   293.1  885.33   307.1  892.28   313.1  894.14
     323  894.53     325  895.04     333  900.24     335  901.14   352.9  907.58
#Mann= 3 , 0 , 0
       0      .1       0   116.4    .045       0   138.1     .08       0
Bank Sta=116.4,138.1
XS Rating Curve= 0 ,0
Exp/Cntr=0.3,0.1

Type RM Length L Ch R = 1 ,7398.7  ,104.6,106.9,109.4
XS GIS Cut Line= 4
     1653042.699      605716.586     1653015.573      605764.329
     1652921.172      605962.897       1652897.3      606046.447
#Sta/Elev= 30
       0  897.03    29.4  889.14    37.3  885.16      49  878.36    64.9  870.19
    72.9  867.34    92.9  865.79   126.9   864.6   190.8  864.12   198.8  863.38
   206.8  860.79   212.8  859.56   216.7  858.85   230.8  858.61   232.8  859.43
   236.8  865.35   238.8  865.77   256.8   866.5   258.8  866.54   262.8  865.75
   266.8  865.98   272.8  867.99   278.7  870.76   288.6  874.52   296.5  878.26
   308.4  883.07   314.3  886.19   324.2  892.96   347.8  910.37   361.7  917.76
#Mann= 3 , 0 , 0
       0     .07       0   212.8    .045       0   232.8     .08       0
Bank Sta=212.8,232.8
XS Rating Curve= 0 ,0
Exp/Cntr=0.3,0.1

Type RM Length L Ch R = 1 ,7291.8  ,34,33.9,34
XS GIS Cut Line= 2
     1652951.554      605707.906     1652758.411       606010.64
#Sta/Elev= 30
       0   893.1       6  890.73      14  886.77    35.9  873.05    41.9   869.8
    51.9  866.47    57.8  864.98    67.8  864.39    95.8   864.3   125.7  863.58
   163.6  863.35   171.6   863.6   173.6  863.06   181.5  858.32     184  857.51
   187.5  856.76   195.5   857.1     199  857.82   201.5   859.8   203.5  862.29
   205.5   863.8   207.5   864.2   227.4  865.05   253.4  864.73   277.3  865.22
   297.2  866.51   311.2  868.14   323.2  870.46   331.2  872.98   359.1  886.86
#Mann= 3 , 0 , 0
       0     .06       0     184    .045       0     199     .08       0
Bank Sta=184,199
XS Rating Curve= 0 ,0
Exp/Cntr=0.3,0.1