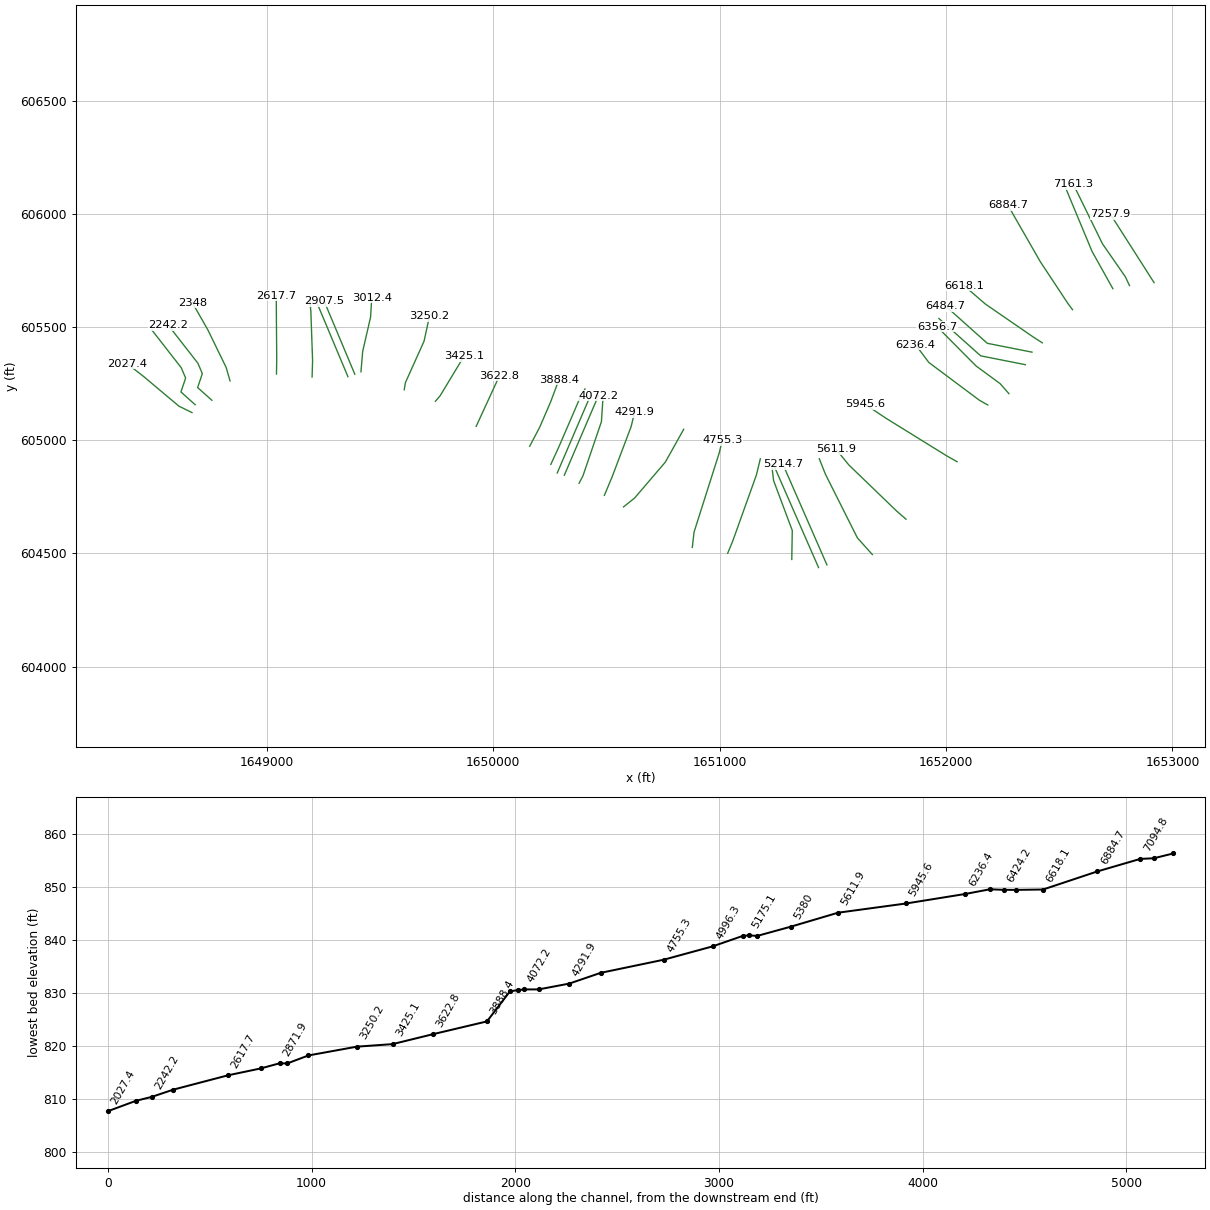
HEC-RAS study NFSHORTCRK.prj: NFSHORTCRK

--- NFSHORTCRK.g01 (geometry) --- (continued)

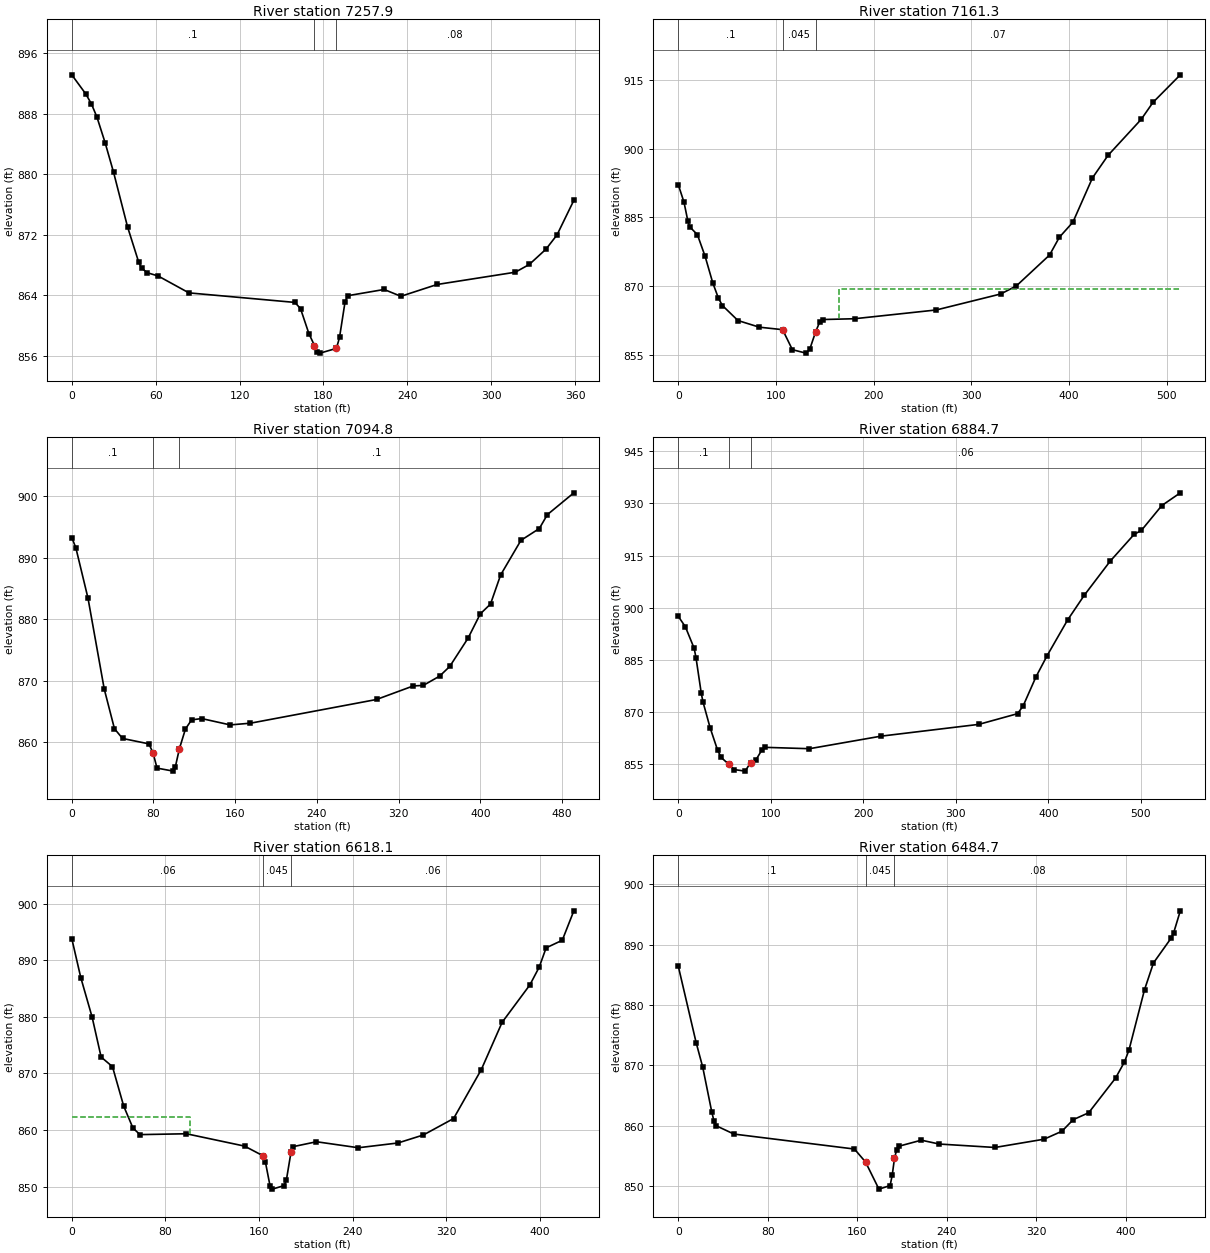
Type RM Length L Ch R = 1 ,7257.9  ,95.7,96.6,97.5
XS GIS Cut Line= 2
     1652919.001       605695.97     1652725.859      605998.704
#Sta/Elev= 30
       0  893.14      10  890.62      14  889.32      18  887.56    23.9  884.14
    29.9  880.26    39.9  873.05    47.9  868.37    49.9  867.62    53.9     867
    61.8  866.56    83.8  864.33   159.6  863.07   163.6  862.25   169.6  858.95
   173.6  857.37   175.6  856.51   177.6  856.37   189.3     857   191.5  858.44
   195.5  863.19   197.5  863.96   223.4  864.78   235.4  863.88   261.3  865.44
   317.2  867.06   327.2  868.08   339.2  870.11   347.1     872   359.1  876.56
#Mann= 3 , 0 , 0
       0      .1       0   173.6    .045       0   189.3     .08       0
Bank Sta=173.6,189.3
XS Rating Curve= 0 ,0
Exp/Cntr=0.3,0.1

Type RM Length L Ch R = 1 ,7161.3  ,68.7,66.5,64.3
XS GIS Cut Line= 4
     1652810.494      605682.949     1652792.048      605722.011
     1652691.137      605867.411     1652562.014      606131.083
#Sta/Elev= 30
       0  892.16     5.9  888.31     9.8  884.26    11.8  882.94    19.6  881.25
    27.5  876.53    35.3  870.78    41.2  867.37    45.2  865.82    61.1  862.55
      83   861.1   106.8  860.56   116.8   856.2   130.7  855.45   134.5  856.24
   140.6  860.09   144.6  862.14   148.6  862.77   180.4  862.94   264.1  864.85
     330  868.33     346  870.08     380  876.81     390  880.67   403.9  883.97
   423.9  893.61   439.9  898.53   473.8  906.36   485.8  910.04   513.8  916.05
#Mann= 3 , 0 , 0
       0      .1       0   106.8    .045       0   140.6     .07       0
#XS Ineff= 2 , 0
                          164.89          869.43
Permanent Ineff=
       F       F
Bank Sta=106.8,140.6
XS Rating Curve= 0 ,0
Exp/Cntr=0.3,0.1

Type RM Length L Ch R = 1 ,7094.8  ,207.8,210.1,211.4
XS GIS Cut Line= 3
     1652736.927      605669.277     1652644.913      605834.208
     1652528.593      606113.721
#Sta/Elev= 30
       0  893.29       4  891.61    15.9  883.42    31.8  868.66    41.8  862.22
    49.7  860.64    75.5  859.76    79.5  858.33    83.5  855.82    99.4  855.33
   101.4  856.02   105.4  858.98   111.3  862.17   117.3  863.66   127.2  863.87
   155.1  862.84     175  863.12   298.4  866.97   334.3  869.17   344.2  869.26
   360.2  870.77   370.1  872.34     388  876.93     400  880.88     410  882.48
   419.9   887.2   439.8  892.83   457.8  894.75   465.7  897.01   491.6  900.55
#Mann= 3 , 0 , 0
       0      .1       0    79.5    .045       0   105.4      .1       0
Bank Sta=79.5,105.4
XS Rating Curve= 0 ,0
Exp/Cntr=0.3,0.1

Type RM Length L Ch R = 1 ,6884.7  ,256.6,266.6,274.5
XS GIS Cut Line= 4
     1652558.758      605576.612     1652539.227      605602.654
     1652416.614      605788.201     1652273.385      606037.767
#Sta/Elev= 30
       0  897.51     7.7   894.5    17.2  888.31    19.2   885.6    24.9  875.36
    26.8  872.83    34.5  865.41    42.5  859.03    46.4   856.9    54.4     855
    60.4  853.42    72.3  852.97    78.2   855.4    84.2   856.3    90.1  858.92
    94.1  859.81   141.8  859.42   219.2  863.03   324.9  866.42   366.8   869.5
   372.8  871.73   386.8  880.16   398.8  886.22   420.8  896.42   438.8  903.53
   466.8  913.34   492.7  921.05   500.7  922.24   522.7  929.37   542.7  933.03
#Mann= 3 , 0 , 0
       0      .1       0    54.4    .045       0    78.2     .06       0
Bank Sta=54.4,78.2
XS Rating Curve= 0 ,0
Exp/Cntr=0.3,0.1

Type RM Length L Ch R = 1 ,6618.1  ,124.4,133.4,138.9
XS GIS Cut Line= 4
     1652425.295      605430.128     1652386.232      605455.084
     1652173.559      605601.569     1652079.158      605682.949
#Sta/Elev= 30
       0  893.81     7.7  886.92    17.4  879.93    25.1  872.88    34.8  871.18
    44.4  864.21    52.3  860.34    58.3  859.18      98  859.33   147.7  857.15
   163.6  855.43   165.5  854.37   169.5  850.11   171.5  849.55   181.4  850.17
   183.4  851.09   187.4  856.05   189.4  857.06   209.2  857.92     245  856.86
   278.8   857.7   300.6  859.12   326.4  862.02   350.1  870.67   367.9  879.02
   391.6  885.62   399.6  888.77   405.5  892.17   419.3  893.51   429.2  898.71
#Mann= 3 , 0 , 0
       0     .06       0   163.6    .045       0   187.4     .06       0
#XS Ineff= 2 , 0
          100.69  862.29
Permanent Ineff=
       F       F
Bank Sta=163.6,187.4
XS Rating Curve= 0 ,0
Exp/Cntr=0.3,0.1

Type RM Length L Ch R = 1 ,6484.7  ,60.5,60.4,64
XS GIS Cut Line= 3
     1652379.722      605388.895     1652182.239      605427.958
     1651997.777      605592.888
#Sta/Elev= 30
       0  886.44      16  873.75    21.9  869.68    29.9  862.33    31.9   860.8
    33.9  859.98    49.8   858.6   157.5  856.12   167.4  853.98   179.4  849.48
   189.4  850.07   191.3  851.81   193.3  854.58   195.3  856.03   197.3  856.59
   217.3  857.59   233.2  856.95   283.1  856.38     327  857.75     343  859.07
     353  860.98   366.9  862.13   390.9  867.87   398.9  870.56   402.9  872.51
   416.8  882.51   424.8  886.95   440.8  891.11   442.8  891.91   448.8  895.58
#Mann= 3 , 0 , 0
       0      .1       0   167.4    .045       0   193.3     .08       0
Bank Sta=167.4,193.3
XS Rating Curve= 0 ,0
Exp/Cntr=0.3,0.1

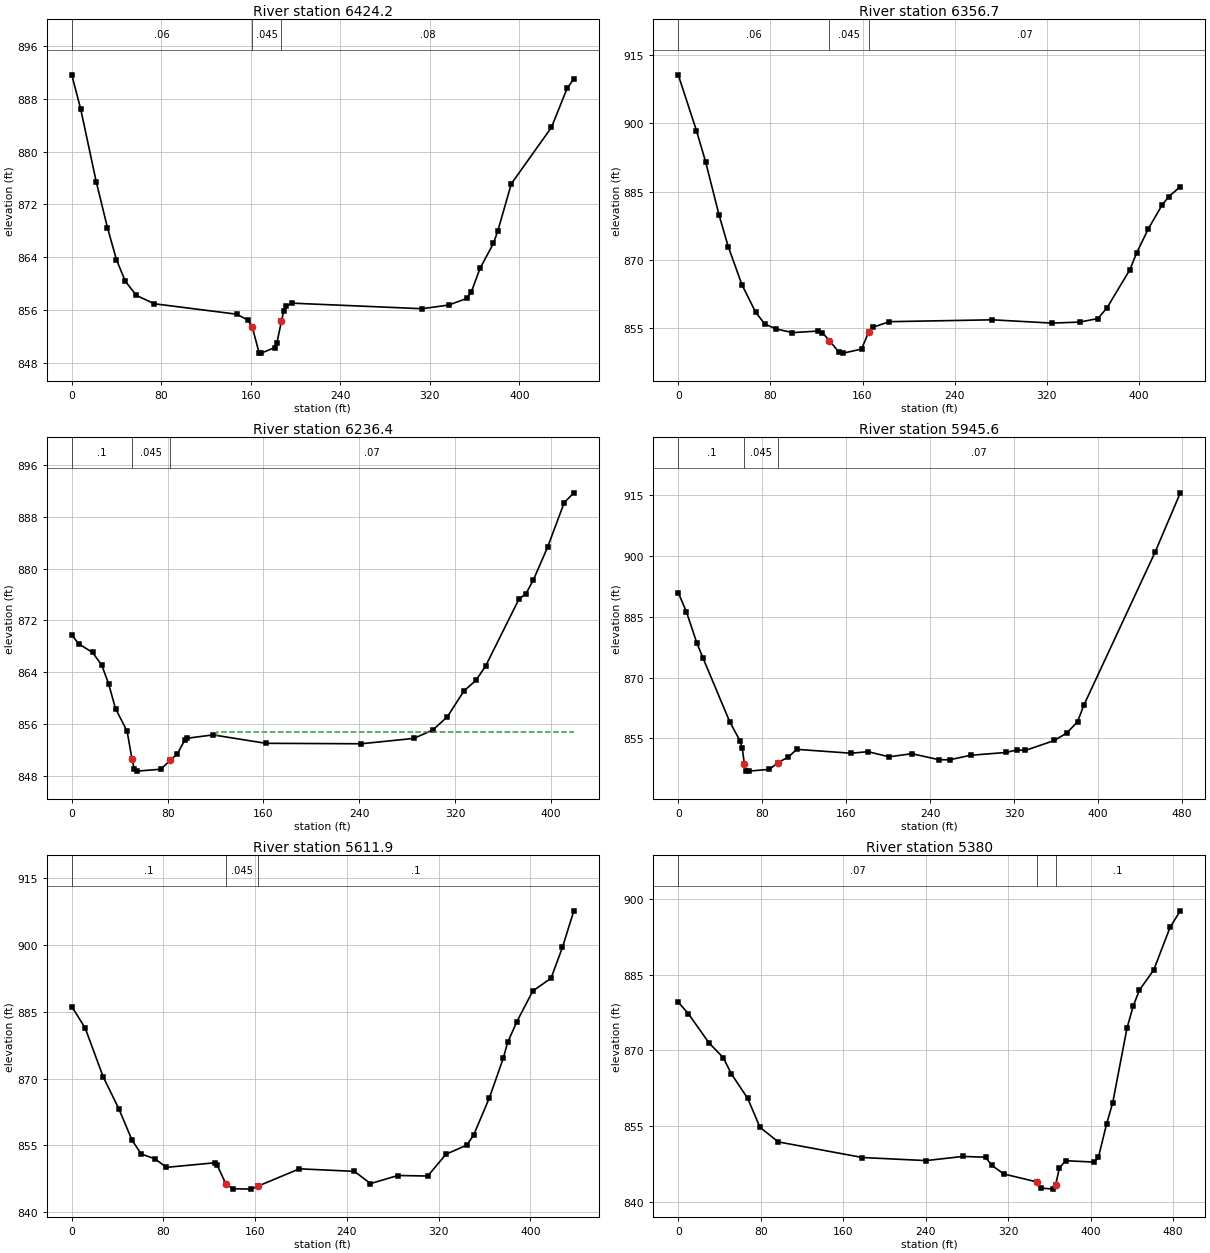
Type RM Length L Ch R = 1 ,6424.2  ,78,67.6,56.5
XS GIS Cut Line= 3
     1652350.425      605333.557     1652152.942      605372.619
     1651968.481       605537.55
#Sta/Elev= 30
       0  891.61       8  886.41    21.9   875.4    31.9  868.48    39.9  863.66
    47.8  860.38    57.8  858.22    73.8  856.96   147.5  855.38   157.5  854.48
   161.4  853.41   167.4  849.56   169.4  849.49   181.3  850.32   183.4  851.08
   187.4  854.29   189.4  855.85   191.3  856.61   197.3  857.05   313.1  856.21
     337  856.77     353  857.76     357  858.67   364.9  862.31   376.9  866.09
   380.9  868.02   392.9  875.12   428.8  883.66   442.8  889.57   448.8     891
#Mann= 3 , 0 , 0
       0     .06       0   161.4    .045       0   187.4     .08       0
Bank Sta=161.4,187.4
XS Rating Curve= 0 ,0
Exp/Cntr=0.3,0.1

Type RM Length L Ch R = 1 ,6356.7  ,119.3,120.2,121
XS GIS Cut Line= 4
     1652277.725      605205.518     1652238.663      605250.006
     1652132.326      605328.131       1651959.8      605501.742
#Sta/Elev= 30
       0  910.66    15.8  898.43    23.7  891.64    35.5  879.84    43.4  872.97
    55.3   864.6    67.2  858.56    75.2  855.96    85.2  854.88    99.2  854.09
   121.2  854.43   125.2  854.06   131.2  852.36   139.2   849.9   143.2  849.59
   159.2  850.48   165.2  854.17   169.2  855.28   183.2  856.49   272.7   856.9
   324.5  856.18   348.4   856.4   364.3  857.17   372.2  859.51   392.1  867.89
   398.1  871.65     408   876.8     420  882.07     426  883.96   435.9  886.11
#Mann= 3 , 0 , 0
       0     .06       0   131.2    .045       0   165.2     .07       0
Bank Sta=131.2,165.2
XS Rating Curve= 0 ,0
Exp/Cntr=0.3,0.1

Type RM Length L Ch R = 1 ,6236.4  ,288.4,290.8,292.2
XS GIS Cut Line= 4
     1652184.409      605155.605     1652147.517      605176.221
     1651923.993      605343.322     1651865.399      605421.447
#Sta/Elev= 30
       0  869.77     5.8  868.38    17.3  867.06      25   865.1    30.7  862.23
    36.5  858.38    46.2  854.87    50.2   850.6    52.2  848.99    54.2  848.71
    74.2     849    82.1  850.37    88.1  851.37    94.1  853.45    96.1  853.79
     118  854.31   161.9  853.01   241.6  852.94   285.5  853.77   301.4  855.08
   313.4  857.11   327.3   861.1   337.3  862.75   345.3  864.93   373.2   875.3
   379.1  876.16   385.1  878.22   397.1  883.33     411  890.23     419  891.73
#Mann= 3 , 0 , 0
       0      .1       0    50.2    .045       0    82.1     .07       0
#XS Ineff= 2 , 0
                          121.16          854.79
Permanent Ineff=
       F       F
Bank Sta=50.2,82.1
XS Rating Curve= 0 ,0
Exp/Cntr=0.3,0.1

Type RM Length L Ch R = 1 ,5945.6  ,337.6,333.7,328.9
XS GIS Cut Line= 4
     1652048.776      604904.954     1652004.288      604929.911
     1651736.276      605095.926      1651642.96      605157.775
#Sta/Elev= 30
       0  890.99     7.8  886.26    17.7  878.57    23.5   874.9      49  859.13
      59  854.32      61  852.51      63  848.69      65  846.96      67  846.91
    86.9  847.35    94.9     849   104.9  850.39   112.9  852.29   164.7  851.33
   180.7  851.72   200.7  850.45   222.6  851.21   248.6  849.72   258.5  849.71
   278.5  850.83   312.4  851.52   322.4  852.14   330.4  852.01   358.3  854.48
   370.3  856.38   380.3  859.11   386.3  863.18   454.2     901   478.2  915.64
#Mann= 3 , 0 , 0
       0      .1       0      63    .045       0    94.9     .07       0
Bank Sta=63,94.9
XS Rating Curve= 0 ,0
Exp/Cntr=0.3,0.1

Type RM Length L Ch R = 1 ,5611.9  ,238.8,231.9,223.3
XS GIS Cut Line= 4
     1651823.081      604651.048     1651781.849      604686.855
      1651570.26      604890.848     1651513.837      604960.293
#Sta/Elev= 30
       0  886.17    11.7  881.34    27.3  870.44      41  863.24    52.7  856.11
    60.6  853.05    72.6  851.97    82.6  850.06   124.6  851.08   126.6  850.69
   134.6  846.25   140.6  845.26   156.6  845.17   162.6  845.86   198.6  849.73
   246.6  849.16   260.6  846.41   284.5  848.23   310.5  848.11   326.5  853.01
   344.5  855.04   350.5  857.27   364.4  865.72   376.4  874.55   380.3  878.14
   388.3  882.79   402.2  889.66   418.1  892.53   428.1  899.49     438  907.66
#Mann= 3 , 0 , 0
       0      .1       0   134.6    .045       0   162.6      .1       0
Bank Sta=134.6,162.6
XS Rating Curve= 0 ,0
Exp/Cntr=0.3,0.1

Type RM Length L Ch R = 1 ,5380    ,167,165.3,163.9
XS GIS Cut Line= 4
     1651674.427      604494.798     1651608.238      604568.583
     1651467.179      604849.616     1651440.052      604917.975
#Sta/Elev= 30
       0  879.56     9.9  877.25    29.7  871.52    43.6  868.58    51.5  865.37
    67.4  860.49    79.3  854.77    97.1  851.88   178.7  848.79   240.4  848.18
   276.2     849   298.1  848.85   304.1  847.25     316  845.52   347.9  843.96
   351.9  842.75   363.8  842.53   366.1  843.34   369.8  846.71   375.8  848.16
   403.6  847.88   407.6   848.8   415.6  855.46   421.5  859.63   435.4  874.44
   441.4  878.77   447.4  881.94   461.3  885.92   477.2   894.4   487.1  897.64
#Mann= 3 , 0 , 0
       0     .07       0   347.9    .045       0   366.1      .1       0
Bank Sta=347.9,366.1
XS Rating Curve= 0 ,0
Exp/Cntr=0.3,0.1

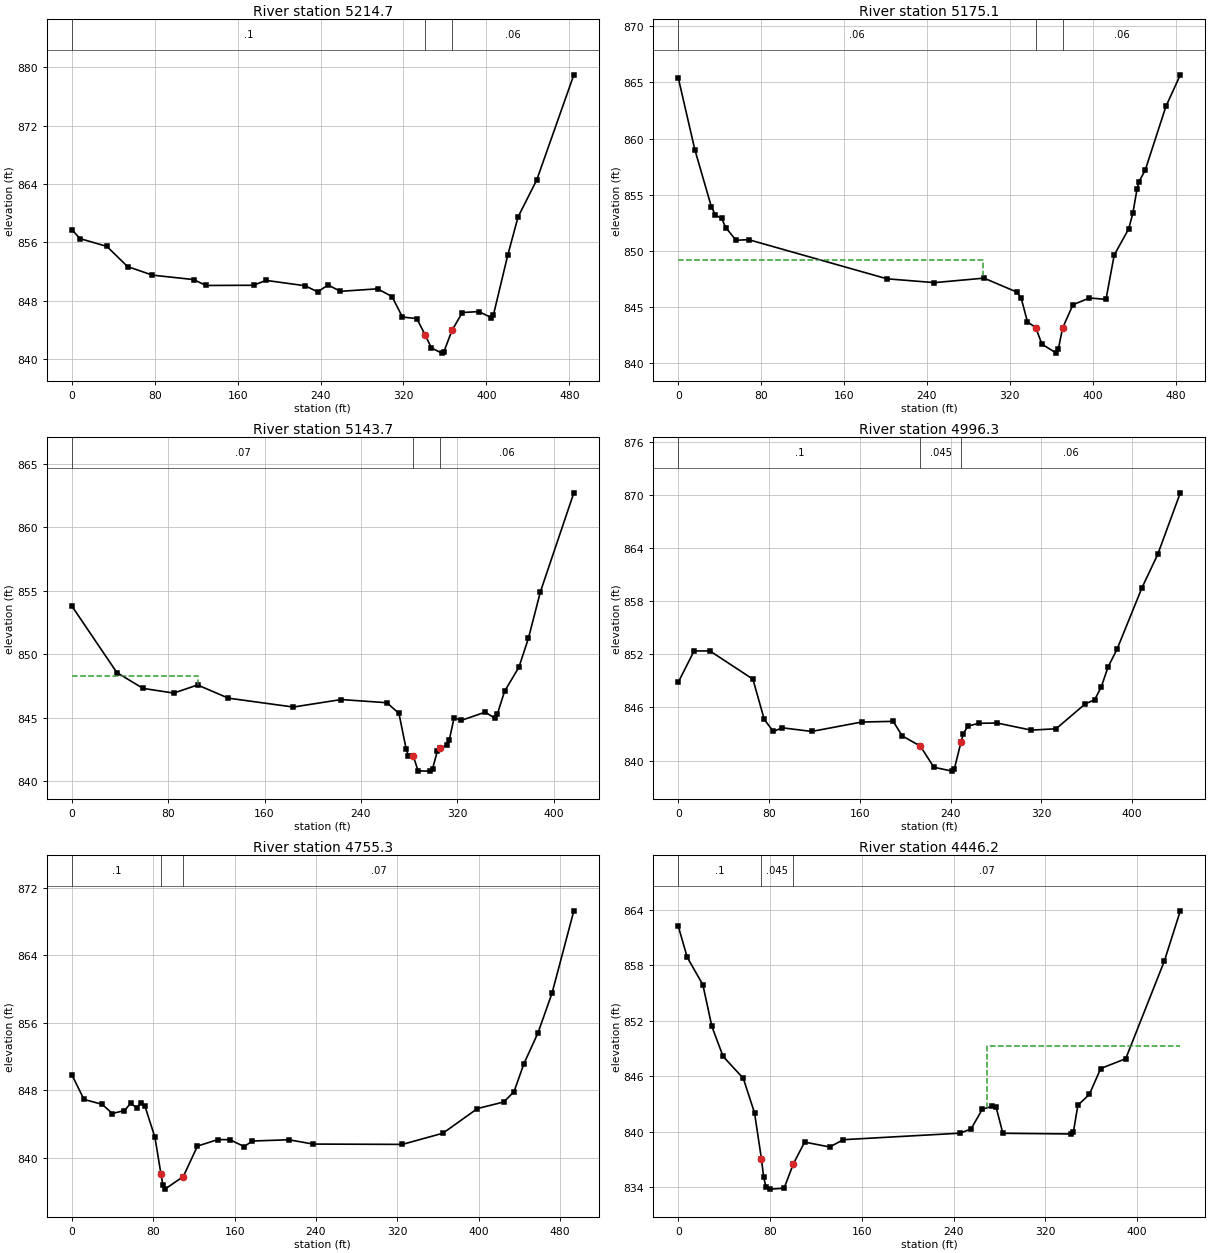
Type RM Length L Ch R = 1 ,5214.7  ,39.6,39.6,39.2
XS GIS Cut Line= 2
     1651473.689      604449.225     1651279.462      604893.018
#Sta/Elev= 30
       0  857.73       8  856.49    33.9  855.42    53.8  852.66    77.8  851.48
   117.6  850.87   129.6  850.06   175.4  850.09   187.4  850.76   225.3  850.02
   237.2  849.18   247.2  850.13   259.2  849.26     295   849.6     309  848.54
     319  845.73   332.9  845.52   340.9  843.29   346.9  841.51   356.8  840.78
   358.8  840.88   366.8  843.89   376.8  846.35   392.7  846.48   404.7  845.66
   406.7  845.95   420.6   854.2   430.6  859.47   448.6  864.54   484.4  878.96
#Mann= 3 , 0 , 0
       0      .1       0   340.9    .045       0   366.8     .06       0
Bank Sta=340.9,366.8
XS Rating Curve= 0 ,0
Exp/Cntr=0.3,0.1

Type RM Length L Ch R = 1 ,5175.1  ,32.7,31.4,30.2
XS GIS Cut Line= 2
     1651436.797      604437.289     1651242.569      604881.083
#Sta/Elev= 30
       0  865.42      16  859.02    31.9  853.95    35.9  853.17    41.9  852.89
    45.8  852.08    55.8  850.94    67.8     851   201.4  847.51   247.2  847.17
     295  847.57   326.9  846.32   330.9  845.78   336.9  843.68   344.9  843.16
   350.9  841.69   364.8  840.89   366.8  841.29   370.8  843.12   380.8   845.2
   396.7   845.8   412.7  845.68   420.6  849.62   434.6  851.96   438.6  853.35
   442.6  855.49   444.6  856.17   450.5  857.18   470.5  862.86   484.4  865.68
#Mann= 3 , 0 , 0
       0     .06       0   344.9    .045       0   370.8     .06       0
#XS Ineff= 2 , 0
          293.79  849.18
Permanent Ineff=
       F       F
Bank Sta=344.9,370.8
XS Rating Curve= 0 ,0
Exp/Cntr=0.3,0.1

Type RM Length L Ch R = 1 ,5143.7  ,166.1,147.4,129
XS GIS Cut Line= 4
     1651318.524      604473.096     1651320.694      604601.135
     1651238.229      604821.404     1651231.718      604874.572
#Sta/Elev= 30
       0   853.8    37.4  848.55    59.1   847.3    84.7  846.93   104.4  847.57
     130  846.53   183.9  845.83   223.7  846.42   261.6  846.17   271.6  845.33
   277.6  842.52   279.5  841.99   283.5  841.97   287.5   840.8   297.3  840.78
   299.5  840.97   303.5  842.35   305.4  842.63   311.4   842.8   313.4  843.24
   317.4  844.99   323.4  844.78   343.3  845.43   351.3  844.94   353.3  845.28
   359.3  847.07   371.2  848.97   379.1  851.25     389   854.9   416.8  862.71
#Mann= 3 , 0 , 0
       0     .07       0   283.5    .045       0   305.4     .06       0
#XS Ineff= 2 , 0
          104.83  848.27
Permanent Ineff=
       F       F
Bank Sta=283.5,305.4
XS Rating Curve= 0 ,0
Exp/Cntr=0.3,0.1

Type RM Length L Ch R = 1 ,4996.3  ,237.8,241,242.1
XS GIS Cut Line= 4
     1651035.321      604500.223     1651058.107      604555.562
     1651162.274       604846.36     1651179.635      604917.975
#Sta/Elev= 30
       0  848.84      14  852.38    27.9  852.38    65.8  849.19    75.8  844.64
    83.8  843.29    91.7   843.7   117.6  843.29   161.5  844.35   189.4  844.43
   197.4  842.78   213.3  841.64   225.2  839.25   241.2  838.81   243.2  839.01
   249.2  842.11   251.2  843.02   255.2   843.9   265.1  844.21     281  844.24
     311  843.44   332.9  843.59   358.8  846.42   366.8  846.85   372.7  848.29
   378.7  850.56   386.7  852.59   408.6  859.51   422.5  863.28   442.4  870.23
#Mann= 3 , 0 , 0
       0      .1       0   213.3    .045       0   249.2     .06       0
Bank Sta=213.3,249.2
XS Rating Curve= 0 ,0
Exp/Cntr=0.3,0.1

Type RM Length L Ch R = 1 ,4755.3  ,316.7,309.1,301.3
XS GIS Cut Line= 4
     1650879.071      604526.265     1650886.666      604593.539
     1650998.429      604945.102     1651011.449       605000.44
#Sta/Elev= 30
       0  849.85      12  846.91    29.9  846.33    39.8  845.24    51.8  845.59
    57.8  846.44    63.7  845.94    67.7  846.43    71.7  846.19    81.7  842.43
    87.6  838.12    89.6  836.71    91.6  836.28   109.6  837.77   123.5  841.38
   143.5  842.15   155.4  842.14   169.4  841.32   177.4  841.98   213.3  842.13
   237.2  841.62   324.9  841.58   364.8  842.91   398.7  845.83   424.6  846.61
   434.6  847.83   444.4  851.16   458.2  854.81   471.9  859.48   493.4  869.26
#Mann= 3 , 0 , 0
       0      .1       0    87.6    .045       0   109.6     .07       0
Bank Sta=87.6,109.6
XS Rating Curve= 0 ,0
Exp/Cntr=0.3,0.1

Type RM Length L Ch R = 1 ,4446.2  ,146.1,154.3,161.7
XS GIS Cut Line= 4
     1650575.251      604705.301      1650624.08      604744.364
     1650759.713      604902.784     1650841.093      605048.183
#Sta/Elev= 30
       0  862.26     7.8  858.89    21.5   855.9    29.3  851.41    39.1  848.16
    56.7  845.79    66.5  842.06    72.5   837.1    74.4  835.13    76.4  834.08
    80.4   833.8    92.3   833.9   100.3  836.52   110.2  838.89     132  838.36
     144  839.15   245.3  839.85   255.2   840.3   265.1  842.44   273.1  842.74
     277  842.72     283  839.84   342.5  839.77   344.5  839.98   348.4  842.88
   358.4  844.05   368.3  846.85   390.1  847.91   423.8  858.48   437.7  863.91
#Mann= 3 , 0 , 0
       0      .1       0    72.5    .045       0   100.3     .07       0
#XS Ineff= 2 , 0
                          268.82          849.29
Permanent Ineff=
       F       F
Bank Sta=72.5,100.3
XS Rating Curve= 0 ,0
Exp/Cntr=0.3,0.1

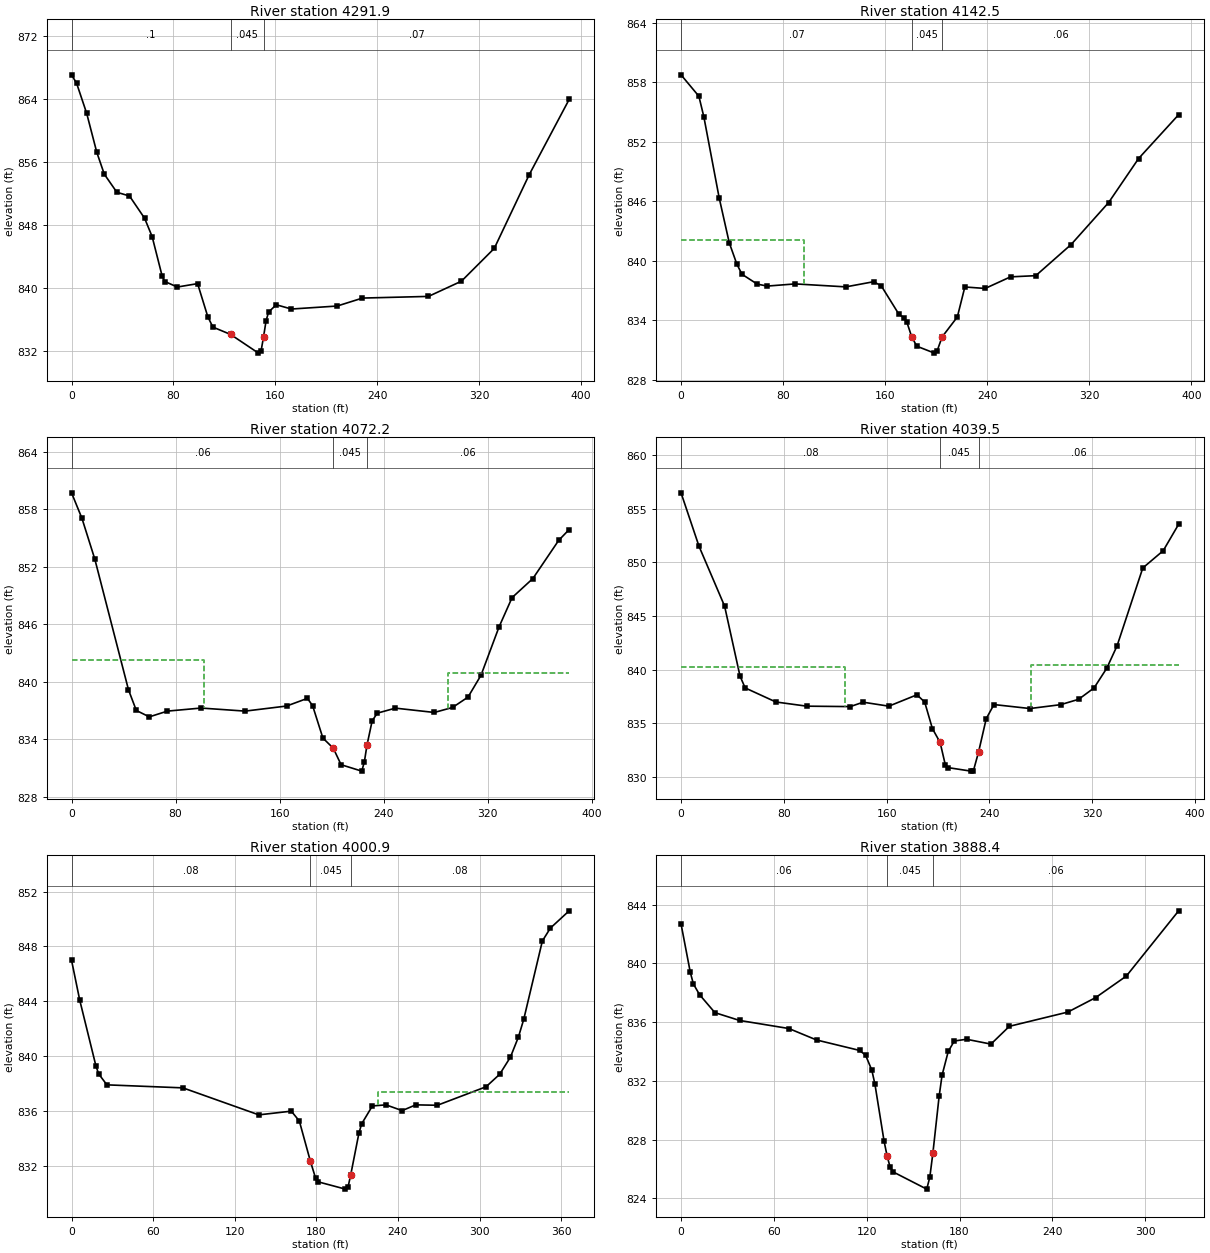
Type RM Length L Ch R = 1 ,4291.9  ,146.2,149.4,150.5
XS GIS Cut Line= 4
     1650490.616        604756.3     1650524.253      604836.595
     1650608.889      605060.119      1650624.08      605123.053
#Sta/Elev= 30
       0  867.05       4  865.97    11.9  862.16    19.8  857.24    25.7  854.46
    35.6  852.16    45.5  851.69    57.4  848.86    63.3  846.54    71.2  841.51
    73.2  840.85    83.1  840.15      99  840.58     107  836.39     111  835.07
   124.9  834.14   146.8  831.77   148.8     832   150.8  833.84   152.8   835.9
   154.8  836.99   160.8   837.9   172.7  837.36   208.6  837.74   228.5  838.75
   280.3  838.96   306.2  840.89     332  845.05   359.4  854.38   390.8  863.93
#Mann= 3 , 0 , 0
       0      .1       0   124.9    .045       0   150.8     .07       0
Bank Sta=124.9,150.8
XS Rating Curve= 0 ,0
Exp/Cntr=0.3,0.1

Type RM Length L Ch R = 1 ,4142.5  ,74.4,70.3,67.6
XS GIS Cut Line= 4
     1650378.854      604809.468     1650396.215      604843.105
     1650477.595       605081.82     1650484.106      605181.647
#Sta/Elev= 30
       0  858.74      14  856.58    17.9   854.5    29.9  846.34    37.8  841.81
    43.8  839.64    47.8  838.63    59.7  837.64    67.6  837.44    89.5  837.66
   129.2  837.36     151  837.88     157  837.46   170.9  834.58   174.9  834.24
   176.9  833.86   180.8  832.34   184.8  831.38   198.7  830.68   200.7  830.88
   204.7  832.32   216.6  834.32   222.5  837.35   238.4   837.2   258.3  838.37
   278.1  838.49   305.8  841.63   335.2  845.86   358.7   850.3   390.1  854.72
#Mann= 3 , 0 , 0
       0     .07       0   180.8    .045       0   204.7     .06       0
#XS Ineff= 2 , 0
           96.55  842.06
Permanent Ineff=
       F       F
Bank Sta=180.8,204.7
XS Rating Curve= 0 ,0
Exp/Cntr=0.3,0.1

Type RM Length L Ch R = 1 ,4072.2  ,32.8,32.7,32.8
XS GIS Cut Line= 2
      1650313.75      604845.275     1650464.357      605197.055
#Sta/Elev= 30
       0   859.7       8  857.04    17.9  852.78    43.8  839.15    49.8     837
    59.8  836.33    73.7  836.93    99.6  837.25   133.5  836.93   165.4  837.46
   181.4  838.26   185.4   837.5   193.3  834.12   201.3  833.06   207.3  831.34
   223.2  830.67   225.2  831.64   227.2  833.37   231.2  835.92   235.2  836.72
   249.1  837.24     279  836.79     293  837.31   304.9  838.39   314.9  840.67
   328.8  845.72   338.8  848.77   354.8  850.76   374.7  854.75   382.7  855.87
#Mann= 3 , 0 , 0
       0     .06       0   201.3    .045       0   227.2     .06       0
#XS Ineff= 2 , 0
          102.07  842.31  289.66           840.9
Permanent Ineff=
       F       F
Bank Sta=201.3,227.2
XS Rating Curve= 0 ,0
Exp/Cntr=0.3,0.1

Type RM Length L Ch R = 1 ,4039.5  ,38.6,38.6,38.5
XS GIS Cut Line= 2
     1650282.283      604855.041     1650434.843      605210.944
#Sta/Elev= 30
       0  856.47      14  851.49    33.9  845.92    45.9   839.4    49.9   838.3
    73.8  836.99    97.8   836.6   131.7  836.56   141.7  836.97   161.7   836.6
   183.6  837.66   189.6  836.98   195.6  834.51   201.6  833.22   205.6  831.16
   207.6  830.88   225.6  830.55   227.5  830.58   231.5  832.32   237.5  835.44
   243.5  836.75   271.5  836.38   295.4  836.74   309.4  837.24   321.4   838.3
   331.3  840.14   339.3  842.22   359.3  849.47   375.2  851.08   387.2  853.54
#Mann= 3 , 0 , 0
       0     .08       0   201.6    .045       0   231.5     .06       0
#XS Ineff= 2 , 0
          127.45  840.29  272.55          840.47
Permanent Ineff=
       F       F
Bank Sta=201.6,231.5
XS Rating Curve= 0 ,0
Exp/Cntr=0.3,0.1

Type RM Length L Ch R = 1 ,4000.9  ,112.3,112.5,112.3
XS GIS Cut Line= 4
     1650254.071      604893.018     1650289.878      604971.143
     1650382.109      605184.902     1650404.896      605226.135
#Sta/Elev= 30
       0  846.99       6  844.09      18  839.25      20  838.69      26   837.9
    81.9  837.68   137.7  835.71   161.6  835.98   167.5  835.26   175.5  832.37
   179.5  831.07   181.4  830.82   201.4  830.29   203.3  830.44   205.3  831.34
   211.3  834.37   213.3  835.05   221.2  836.36   231.2  836.44   243.1  836.02
   253.1  836.44     269  836.41   304.8  837.76   314.8  838.67   322.7  839.92
   328.6  841.39   332.5  842.68   346.2   848.4   352.1  849.34   365.9   850.6
#Mann= 3 , 0 , 0
       0     .08       0   175.5    .045       0   205.3     .08       0
#XS Ineff= 2 , 0
                          225.66           837.4
Permanent Ineff=
       F       F
Bank Sta=175.5,205.3
XS Rating Curve= 0 ,0
Exp/Cntr=0.3,0.1

Type RM Length L Ch R = 1 ,3888.4  ,266.1,265.6,264.4
XS GIS Cut Line= 4
     1650160.755      604973.314     1650205.243      605057.949
     1650252.986      605168.626     1650289.878      605267.367
#Sta/Elev= 30
       0  842.68       6  839.38       8  838.59      12  837.86    21.9  836.64
    37.8  836.11    69.7  835.56    87.6  834.78   115.4  834.07   119.3  833.74
   123.3  832.73   125.3  831.78   131.2  827.91   133.2  826.88   135.1  826.14
   137.1   825.8   158.8  824.63   160.8  825.45   162.8  827.11   166.8  830.94
   168.7  832.38   172.7     834   176.6  834.71   184.5  834.83   200.3   834.5
   212.2  835.71     250  836.68   267.9  837.66   287.8  839.13   321.6  843.57
#Mann= 3 , 0 , 0
       0     .06       0   133.2    .045       0   162.8     .06       0
Bank Sta=133.2,162.8
XS Rating Curve= 0 ,0
Exp/Cntr=0.3,0.1

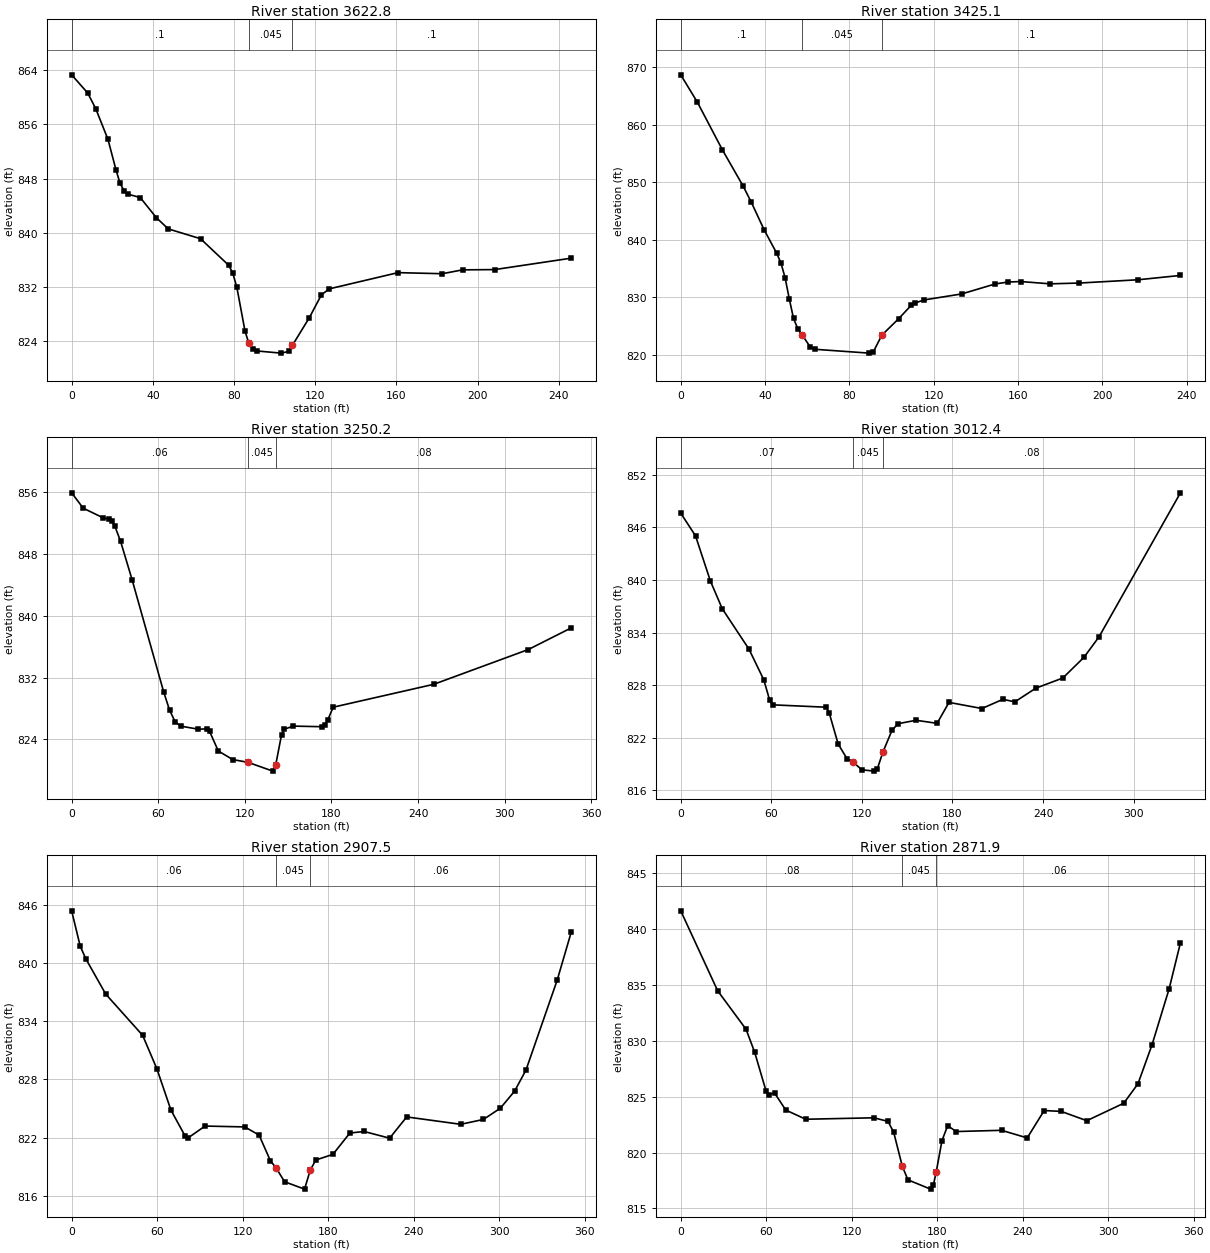
Type RM Length L Ch R = 1 ,3622.8  ,199.8,197.7,195.3
XS GIS Cut Line= 2
      1649924.21      605061.204     1650027.291      605284.728
#Sta/Elev= 30
       0  863.32     7.9  860.64    11.9   858.3    17.9  853.78    21.8  849.33
    23.8  847.33    25.8   846.2    27.8  845.69    33.8  845.19    41.7  842.23
    47.6  840.56    63.5  839.11    77.4  835.18    79.4  834.03    81.4  831.92
    85.4  825.49    87.3  823.65    89.3  822.89    91.3  822.53   103.2  822.21
   107.2  822.48   108.8  823.38   117.1  827.44   123.1  830.84     127  831.71
   160.8   834.1   182.6  833.94   192.6  834.51   208.4  834.55   246.2  836.24
#Mann= 3 , 0 , 0
       0      .1       0    87.3    .045       0   108.8      .1       0
Bank Sta=87.3,108.8
XS Rating Curve= 0 ,0
Exp/Cntr=0.3,0.1

Type RM Length L Ch R = 1 ,3425.1  ,171.9,175,177.5
XS GIS Cut Line= 3
     1649744.088      605171.881     1649764.705      605195.753
     1649871.041      605371.534
#Sta/Elev= 30
       0  868.66     7.9   863.9    19.7  855.67    29.6  849.34    33.5  846.51
    39.5  841.79    45.5  837.69    47.5  836.01    49.5  833.43    51.5  829.72
    53.5  826.36    55.5  824.59    57.5  823.54    61.5  821.37    63.5  821.01
    89.4  820.34    91.4  820.61    95.4  823.47   103.4  826.33   109.3  828.64
   111.3  829.06   115.3  829.57   133.3  830.62   149.2  832.36   155.2  832.68
   161.2  832.77   175.2  832.37   189.1  832.51     217  833.08     237  833.83
#Mann= 3 , 0 , 0
       0      .1       0    57.5    .045       0    95.4      .1       0
Bank Sta=57.5,95.4
XS Rating Curve= 0 ,0
Exp/Cntr=0.3,0.1

Type RM Length L Ch R = 1 ,3250.2  ,233.4,237.8,242.2
XS GIS Cut Line= 4
     1649606.284      605222.879      1649611.71      605254.346
     1649694.175      605437.723     1649718.047        605548.4
#Sta/Elev= 30
       0  855.95       8  853.96      22  852.69    25.9  852.54    27.9  852.26
    29.9  851.64    33.9  849.66    41.9  844.67    63.8   830.1    67.8  827.79
    71.8  826.22    75.7  825.69    87.7   825.3    93.6  825.33    95.6     825
   101.6  822.47   111.6  821.36   122.2     821   139.4  819.86   141.4  820.69
   145.4  824.56   147.4  825.29   153.4   825.7   173.3  825.62   175.3  825.79
   177.3  826.44   181.2  828.15   250.9  831.12   316.4  835.63   346.2  838.44
#Mann= 3 , 0 , 0
       0     .06       0   122.2    .045       0   141.4     .08       0
Bank Sta=122.2,141.4
XS Rating Curve= 0 ,0
Exp/Cntr=0.3,0.1

Type RM Length L Ch R = 1 ,3012.4  ,90.6,104.9,119.8
XS GIS Cut Line= 4
     1649415.312       605302.09     1649422.908       605392.15
      1649457.63      605542.975     1649463.055      605628.695
#Sta/Elev= 30
       0  847.62     9.8  845.03    19.6   839.9    27.5  836.72    45.2  832.11
      55  828.62    58.9  826.29    60.9  825.76    96.3  825.49    98.3  824.86
   104.3  821.28   110.2   819.6   114.2  819.22     120  818.35   128.1   818.2
   130.1   818.4     134  820.41     140  822.88     144  823.61   155.9     824
   169.8  823.65   177.7  826.04   199.5  825.34   213.4  826.39   221.3   826.1
   235.2  827.66   253.1  828.82   267.1  831.18   277.1  833.52     331  849.94
#Mann= 3 , 0 , 0
       0     .07       0   114.2    .045       0     134     .08       0
Bank Sta=114.2,134
XS Rating Curve= 0 ,0
Exp/Cntr=0.3,0.1

Type RM Length L Ch R = 1 ,2907.5  ,35.1,35.6,35.4
XS GIS Cut Line= 2
     1649388.185      605291.239     1649252.552       605614.59
#Sta/Elev= 30
       0  845.36       6  841.72      10   840.4    23.9  836.78    49.8  832.53
    59.8  829.08    69.7  824.81    79.7  822.13    81.7  821.96    93.6  823.18
   121.5  823.09   131.5  822.25   139.5  819.59   143.4  818.88   149.4  817.44
   163.4  816.68   167.4  818.63   171.3  819.68   183.3  820.26   195.2  822.46
   205.2  822.62   223.1  821.93   235.1  824.12     273  823.36   288.9  823.86
   300.8  825.02   310.8  826.78   318.8  828.96   340.7  838.23   350.6   843.2
#Mann= 3 , 0 , 0
       0     .06       0   143.4    .045       0   167.4     .06       0
Bank Sta=143.4,167.4
XS Rating Curve= 0 ,0
Exp/Cntr=0.3,0.1

Type RM Length L Ch R = 1 ,2871.9  ,102.8,94.5,85.5
XS GIS Cut Line= 2
     1649357.804      605280.388      1649222.17      605603.739
#Sta/Elev= 30
       0  841.62    25.9  834.47    45.8  831.03    51.8     829    59.8  825.53
    61.8  825.18    65.8  825.33    73.7   823.8    87.7  822.98   135.5  823.11
   145.4  822.79   149.4  821.82   155.4   818.8   159.4  817.56   175.3  816.73
   177.3  817.12   179.3   818.3   183.3  821.07   187.3  822.41   193.2  821.88
   225.1  821.99   243.1  821.31     255  823.76     267  823.68   284.9  822.85
   310.8  824.41   320.8  826.15   330.7  829.65   342.7  834.66   350.6  838.76
#Mann= 3 , 0 , 0
       0     .08       0   155.4    .045       0   179.3     .06       0
Bank Sta=155.4,179.3
XS Rating Curve= 0 ,0
Exp/Cntr=0.3,0.1

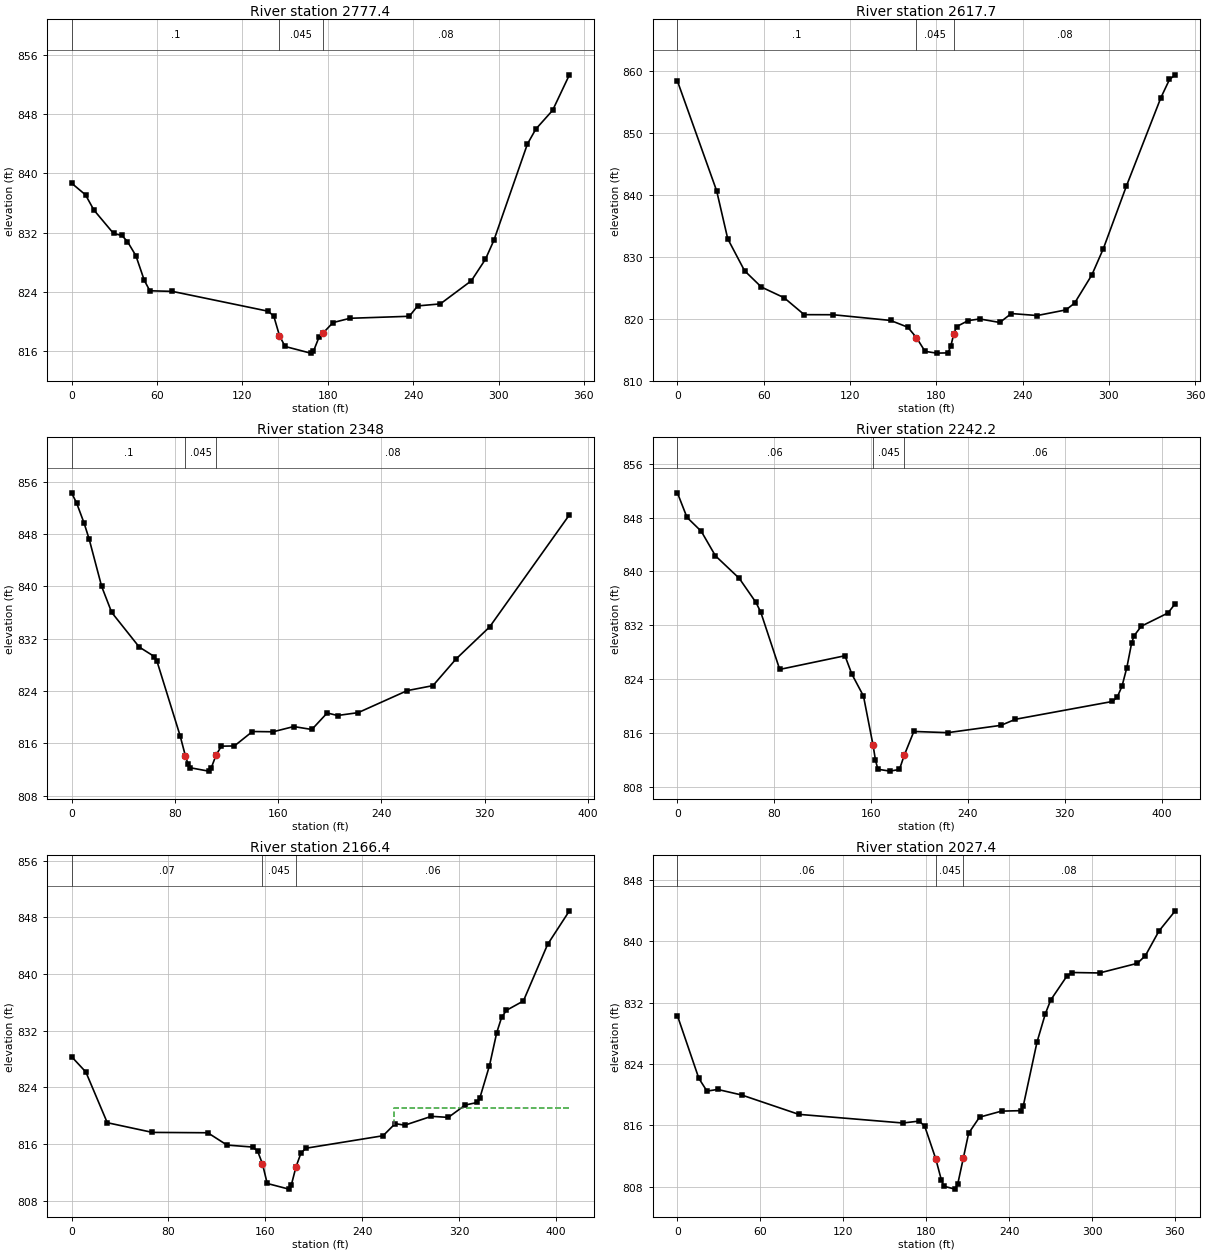
Type RM Length L Ch R = 1 ,2777.4  ,160.1,159.7,158.5
XS GIS Cut Line= 4
     1649199.383      605279.303     1649201.554      605352.003
     1649193.958      605567.932     1649188.533      605628.695
#Sta/Elev= 30
       0  838.67     9.8  837.09    15.7  835.04    29.5  831.88    35.4  831.61
    39.3  830.78    45.2  828.88    51.1  825.56      55  824.15    70.8  824.07
   138.2  821.39   142.1  820.72   146.1  818.09     150  816.64   167.9  815.74
   169.9  815.96   173.8  817.86   176.7  818.45   183.7  819.86   195.6  820.44
   237.3  820.71   243.2  822.11   259.1  822.38   280.9   825.5   290.8   828.4
   296.7  830.94   320.3  843.95   326.2  845.96     338  848.49   349.8  853.28
#Mann= 3 , 0 , 0
       0      .1       0   146.1    .045       0   176.7     .08       0
Bank Sta=146.1,176.7
XS Rating Curve= 0 ,0
Exp/Cntr=0.3,0.1

Type RM Length L Ch R = 1 ,2617.7  ,259.1,269.7,279.3
XS GIS Cut Line= 3
     1649042.048      605292.324     1649043.133      605358.513
     1649040.963      605638.461
#Sta/Elev= 30
       0  858.32    27.3  840.61      35  832.88    46.7  827.73    58.4   825.1
    74.2  823.38    88.2  820.65   108.2  820.64   148.2  819.72   160.2  818.63
   166.2  816.96   172.2  814.74   180.2  814.45   188.2  814.49   190.2  815.65
   192.2  817.55   194.2  818.73   202.2  819.69   210.2  819.96   224.2  819.39
   232.2  820.83   250.2  820.51   270.2  821.42   276.2  822.51   288.2  827.05
   296.2  831.29   312.2  841.36   336.2  855.62   342.2  858.56   346.2  859.31
#Mann= 3 , 0 , 0
       0      .1       0   166.2    .045       0   192.2     .08       0
Bank Sta=166.2,192.2
XS Rating Curve= 0 ,0
Exp/Cntr=0.3,0.1

Type RM Length L Ch R = 1 ,2348    ,106.7,105.7,105
XS GIS Cut Line= 4
      1648836.97      605261.942     1648819.609      605321.621
     1648738.229      605488.721     1648669.869      605608.079
#Sta/Elev= 30
       0  854.31     3.9  852.76     9.7  849.68    13.6  847.25    23.3  839.99
    31.1  836.01    52.4  830.72    64.2  829.25    66.2  828.52    84.1  817.13
    88.1  814.12    90.1  812.87    92.1  812.24   106.1  811.73   108.1  812.18
   112.1  814.26   116.1  815.55   126.1  815.58   140.1  817.79   156.1  817.75
   172.1  818.55   186.1   818.1     198  820.63     206  820.24     222  820.68
     260  824.05   279.9  824.81   297.8  828.89   323.8  833.79   385.6  850.94
#Mann= 3 , 0 , 0
       0      .1       0    88.1    .045       0   112.1     .08       0
Bank Sta=88.1,112.1
XS Rating Curve= 0 ,0
Exp/Cntr=0.3,0.1

Type RM Length L Ch R = 1 ,2242.2  ,75.9,75.9,75.6
XS GIS Cut Line= 6
     1648756.675      605176.221     1648693.741      605232.645
     1648711.102      605283.643     1648714.357      605294.494
     1648694.826      605340.067     1648564.618      605507.168
#Sta/Elev= 30
       0  851.68     7.9  848.04    19.7  845.97    31.4  842.33    51.1  838.98
    64.9   835.4    68.8  833.99    84.5  825.46   138.4  827.49   144.1  824.76
   153.7   821.5   161.6  814.21   163.6  811.98   165.6  810.64   175.5  810.36
   183.4  810.61   187.4  812.73   195.3  816.25   223.3  816.07   267.3  817.16
   279.2  818.06   359.2   820.7   363.2  821.32   367.2  822.95   371.2  825.72
   375.2   829.4   377.2  830.46   383.2  831.88   405.2  833.84   411.2  835.23
#Mann= 3 , 0 , 0
       0     .06       0   161.6    .045       0   187.4     .06       0
Bank Sta=161.6,187.4
XS Rating Curve= 0 ,0
Exp/Cntr=0.3,0.1

Type RM Length L Ch R = 1 ,2166.4  ,127.9,139,149.1
XS GIS Cut Line= 6
      1648682.89       605156.69     1648619.956      605213.114
     1648637.317      605264.112     1648640.573      605274.963
     1648621.041      605320.536     1648490.833      605487.636
#Sta/Elev= 30
       0  828.35    11.8  826.18    29.5  819.02    66.8  817.65   112.5   817.6
   128.4  815.86   149.7  815.58   153.7     815   157.7   813.2   161.6  810.44
   179.5  809.64   181.5  810.21   185.4   812.8   189.4  814.69   193.4  815.41
   257.3  817.18   267.3  818.89   275.2  818.67   297.2  819.92   311.2  819.77
   325.2  821.52   335.2  821.88   337.2   822.5   345.2  827.09   351.2  831.75
   355.2  833.89   359.2  834.89   373.2  836.21   393.2   844.2   411.2  848.94
#Mann= 3 , 0 , 0
       0     .07       0   157.7    .045       0   185.4     .06       0
#XS Ineff= 2 , 0
                          266.21          821.12
Permanent Ineff=
       F       F
Bank Sta=157.7,185.4
XS Rating Curve= 0 ,0
Exp/Cntr=0.3,0.1

Type RM Length L Ch R = 1 ,2027.4  ,367.7,377,385.9
XS GIS Cut Line= 4
     1648668.784      605121.968     1648611.276       605150.18
     1648455.026      605281.473     1648382.326      605337.897
#Sta/Elev= 30
       0  830.31    15.5  822.12    21.4  820.45    29.1  820.67    46.6  819.94
    87.8  817.42   163.1  816.29     175  816.54     179  815.84   186.9  811.63
   190.9  808.91   192.8  808.04   200.8  807.66   202.8   808.3   206.9  811.73
   210.7  814.95   218.6  817.05   234.5  817.84   248.3   817.9   250.3  818.56
   260.2  826.86   266.2  830.54   270.1  832.34   281.8  835.46   285.8  835.93
   305.4  835.87   332.8  837.13   338.6  838.13   348.4  841.34   360.2  843.98
#Mann= 3 , 0 , 0
       0     .06       0   186.9    .045       0   206.9     .08       0
Bank Sta=186.9,206.9
XS Rating Curve= 0 ,0
Exp/Cntr=0.3,0.1