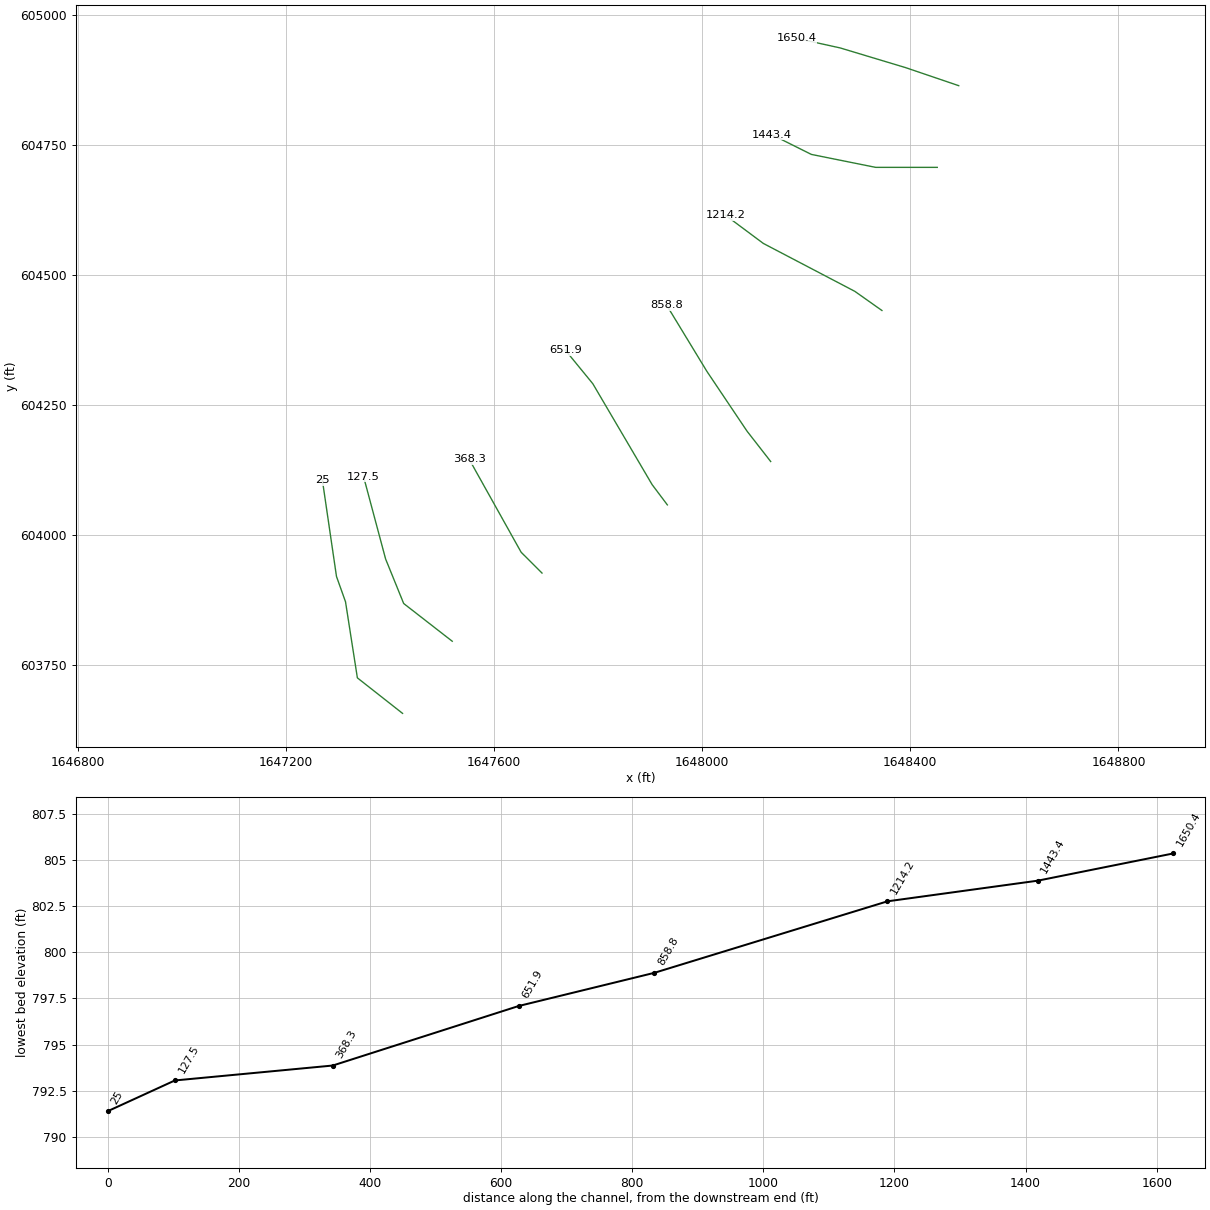
HEC-RAS study NFSHORTCRK.prj: NFSHORTCRK

--- NFSHORTCRK.g01 (geometry) --- (continued)

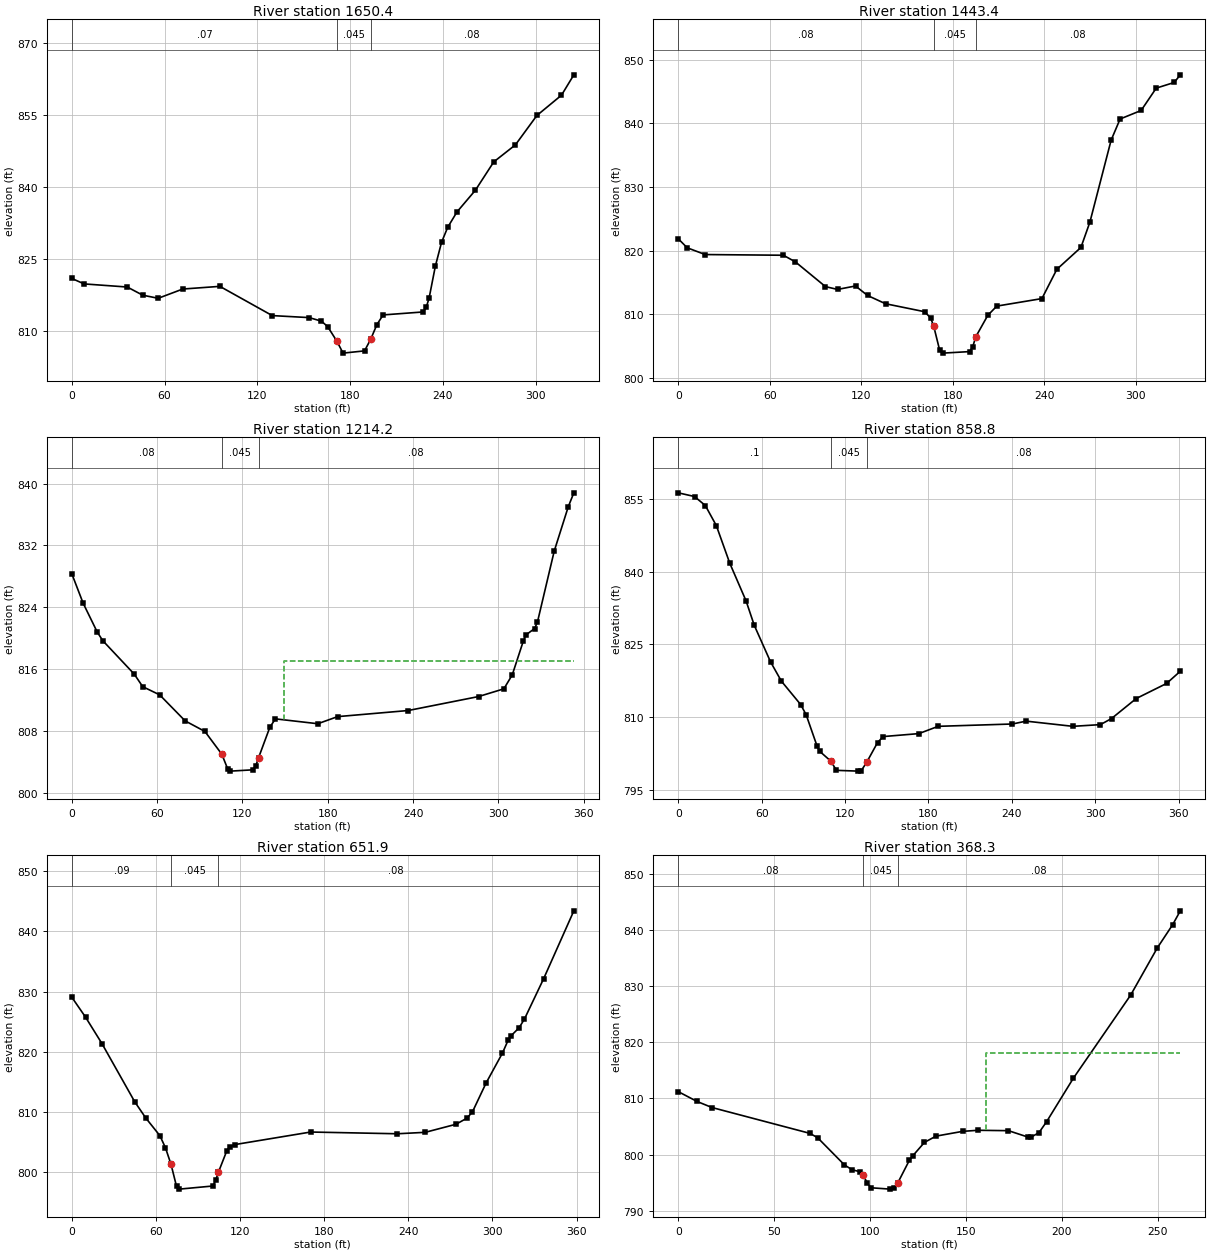
Type RM Length L Ch R = 1 ,1650.4  ,204.8,207,209.1
XS GIS Cut Line= 4
     1648493.003      604864.807     1648391.007      604899.529
     1648265.139      604937.506     1648181.588      604955.952
#Sta/Elev= 30
       0  820.95       8  819.81    35.9  819.16    45.9  817.46    55.9  816.81
    71.8  818.74    95.8   819.3   129.7   813.2   153.6  812.78   161.5  812.04
   165.5  810.92   171.5  807.86   175.5  805.37   189.4  805.84   193.4  808.28
   197.4  811.32   201.4  813.34   227.3  813.96   229.3  814.92   231.2  816.91
   235.2   823.5   239.2  828.48   243.2  831.62   249.2  834.83   261.1  839.35
     273  845.27     287  848.82   300.9  854.95   316.8  859.18   324.8  863.43
#Mann= 3 , 0 , 0
       0     .07       0   171.5    .045       0   193.4     .08       0
Bank Sta=171.5,193.4
XS Rating Curve= 0 ,0
Exp/Cntr=0.3,0.1

Type RM Length L Ch R = 1 ,1443.4  ,236,229.2,221.4
XS GIS Cut Line= 4
     1648451.771      604707.471     1648333.498      604707.471
       1648209.8      604732.428     1648133.845      604770.406
#Sta/Elev= 30
       0  821.86     5.9  820.44    17.7  819.38      69  819.27    76.9  818.22
    96.6  814.34   104.5   813.9   116.3  814.44   124.2  812.95     136  811.65
   161.6   810.4   165.6  809.42   167.6  808.13   171.5  804.36   173.5  803.89
   191.2  804.13   193.2  804.88   195.2  806.45   203.1  809.83     209  811.28
   238.6  812.46   248.4  817.06   264.2   820.5   270.1  824.49     284  837.35
   289.9  840.68   303.7  842.02   313.6  845.53   325.4  846.42   329.4  847.62
#Mann= 3 , 0 , 0
       0     .08       0   167.6    .045       0   195.2     .08       0
Bank Sta=167.6,195.2
XS Rating Curve= 0 ,0
Exp/Cntr=0.3,0.1

Type RM Length L Ch R = 1 ,1214.2  ,366.2,355.5,344.7
XS GIS Cut Line= 4
     1648345.434      604431.864      1648293.35      604468.756
     1648117.569      604560.987     1648044.869      604615.241
#Sta/Elev= 30
       0  828.35       8  824.52      18  820.75    21.9  819.65    43.9  815.34
    49.9  813.71    61.8  812.65    79.7  809.28    93.6  807.91   105.5  804.96
   109.5  803.11   111.5  802.77   127.4  802.94   129.3  803.41   131.3  804.49
   139.3  808.47   143.2  809.54     173  808.91   186.9  809.83   236.5  810.62
     286  812.43   303.8  813.43   309.7  815.24   317.6  819.69   319.5  820.44
   325.4  821.24   327.4  822.07   339.2  831.27   349.1  837.03     353  838.82
#Mann= 3 , 0 , 0
       0     .08       0   105.5    .045       0   131.3     .08       0
#XS Ineff= 2 , 0
                          149.16          817.09
Permanent Ineff=
       F       F
Bank Sta=105.5,131.3
XS Rating Curve= 0 ,0
Exp/Cntr=0.3,0.1

Type RM Length L Ch R = 1 ,858.8   ,208.1,206.9,205.4
XS GIS Cut Line= 4
     1648131.675      604141.065     1648086.102      604199.659
     1648009.062      604314.676     1647932.022      604441.629
#Sta/Elev= 30
       0  856.23    11.7  855.47    19.5  853.61    27.4  849.48    37.1  841.71
    48.8  833.96    54.7  828.93    66.4  821.41    74.2  817.43    88.1   812.6
      92  810.52    99.9  804.03   101.9  802.94   109.8  800.94   113.8  799.05
   129.6  798.89   131.6  798.97   135.5  800.67   143.4  804.78   147.4  806.01
   173.1  806.62     187  808.12   240.4   808.6   250.3  809.19   283.9  808.12
   303.7  808.47   311.7  809.72   329.5  813.85   351.3  816.95   361.2  819.47
#Mann= 3 , 0 , 0
       0      .1       0   109.8    .045       0   135.5     .08       0
Bank Sta=109.8,135.5
XS Rating Curve= 0 ,0
Exp/Cntr=0.3,0.1

Type RM Length L Ch R = 1 ,651.9   ,283.9,283.6,282.9
XS GIS Cut Line= 4
     1647933.107      604057.515      1647903.81      604096.577
     1647789.878      604290.805      1647736.71      604355.909
#Sta/Elev= 30
       0  829.06     9.8  825.74    21.5  821.34    44.9  811.64    52.8  808.93
    62.8  806.01    66.8  803.99    70.8  801.21    74.7  797.56    76.7  797.09
   100.6  797.61   102.6  798.53   104.6  799.91   110.6  803.49   112.6  804.13
   116.6  804.52   170.4   806.6   232.2  806.31   252.1  806.55     274  807.89
   281.8   808.9   285.7  809.92   295.5  814.76   307.2  819.76   311.2  821.88
   313.1  822.58     319  823.95   322.9  825.43   336.6  832.16   358.1  843.44
#Mann= 3 , 0 , 0
       0     .09       0    70.8    .045       0   104.6     .08       0
Bank Sta=70.8,104.6
XS Rating Curve= 0 ,0
Exp/Cntr=0.3,0.1

Type RM Length L Ch R = 1 ,368.3   ,243.5,240.8,237.9
XS GIS Cut Line= 3
     1647692.222      603926.221     1647652.074      603966.369
     1647552.248      604145.406
#Sta/Elev= 30
       0  811.21     9.8  809.46    17.6  808.38    68.7  803.78    72.7     803
    86.6  798.19    90.6  797.31    94.6  796.97    96.6   796.3    98.6  794.88
   100.6   794.1   110.5  793.86   112.5  794.04   114.5  794.98   120.5  798.98
   122.4  799.83   128.4  802.18   134.4  803.29   148.3  804.14   156.3  804.33
   172.2  804.26   182.2  803.14   184.2  803.15   188.1  803.91   192.1  805.87
     206  813.58   235.9  828.38   249.8  836.78   257.8  840.91   261.8  843.38
#Mann= 3 , 0 , 0
       0     .08       0    96.6    .045       0   114.5     .08       0
#XS Ineff= 2 , 0
                           160.5          818.16
Permanent Ineff=
       F       F
Bank Sta=96.6,114.5
XS Rating Curve= 0 ,0
Exp/Cntr=0.3,0.1

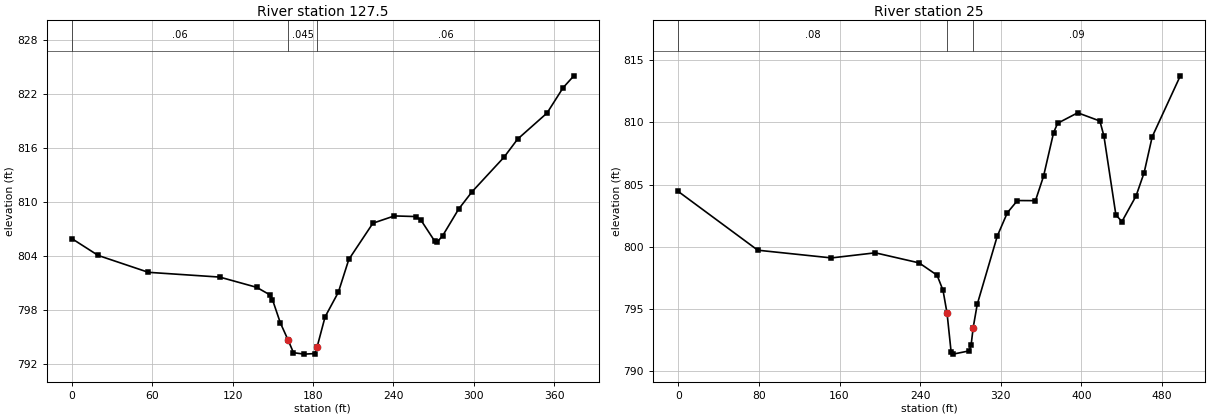
Type RM Length L Ch R = 1 ,127.5   ,103.4,102.5,101.4
XS GIS Cut Line= 4
     1647519.696      603794.928      1647426.38      603867.628
     1647391.658      603953.348      1647349.34      604111.768
#Sta/Elev= 30
       0  805.92    19.7  804.04    57.2  802.16   110.4  801.63     138  800.49
   147.8  799.66   149.8  799.13   155.7  796.53   161.6  794.58   165.5  793.21
   173.4  793.05   181.3  793.11   183.2  793.88   189.1   797.2     199  799.94
   206.8  803.59   224.8  807.63   240.8  808.44   256.8  808.37   260.8  807.94
   270.8  805.66   272.8  805.54   276.8  806.22   288.8   809.2   298.8  811.13
   322.8     815   332.8  816.99   354.8   819.9   366.8  822.72   374.8  824.04
#Mann= 3 , 0 , 0
       0     .06       0   161.6    .045       0   183.2     .06       0
Bank Sta=161.6,183.2
XS Rating Curve= 0 ,0
Exp/Cntr=0.3,0.1

Type RM Length L Ch R = 1 ,25      ,27.1,25,22.7
XS GIS Cut Line= 5
      1647424.21      603656.039     1647337.404      603724.399
     1647314.618      603870.883     1647297.257      603919.711
      1647270.13      604105.258
#Sta/Elev= 30
       0  804.45    78.9  799.73     152  799.11   195.5  799.52     239  798.71
   256.8  797.72   262.7   796.5   266.7  794.66   270.7  791.57   272.7  791.38
   288.6  791.64   290.6  792.14   292.6   793.5   296.6  795.37   316.5  800.86
   326.5  802.74   336.5  803.72   354.4  803.71   362.4  805.67   372.4  809.18
   376.4  809.93   396.3  810.77   418.3  810.11   422.3  808.91   434.2  802.56
   440.2  802.03   454.2  804.09   462.2  805.96   470.2  808.84   498.1  813.74
#Mann= 3 , 0 , 0
       0     .08       0   266.7    .045       0   292.6     .09       0
Bank Sta=266.7,292.6
XS Rating Curve= 0 ,0
Exp/Cntr=0.3,0.1

Chan Stop Cuts=-1
Use User Specified Reach Order=0
Composite Channel Slope=5